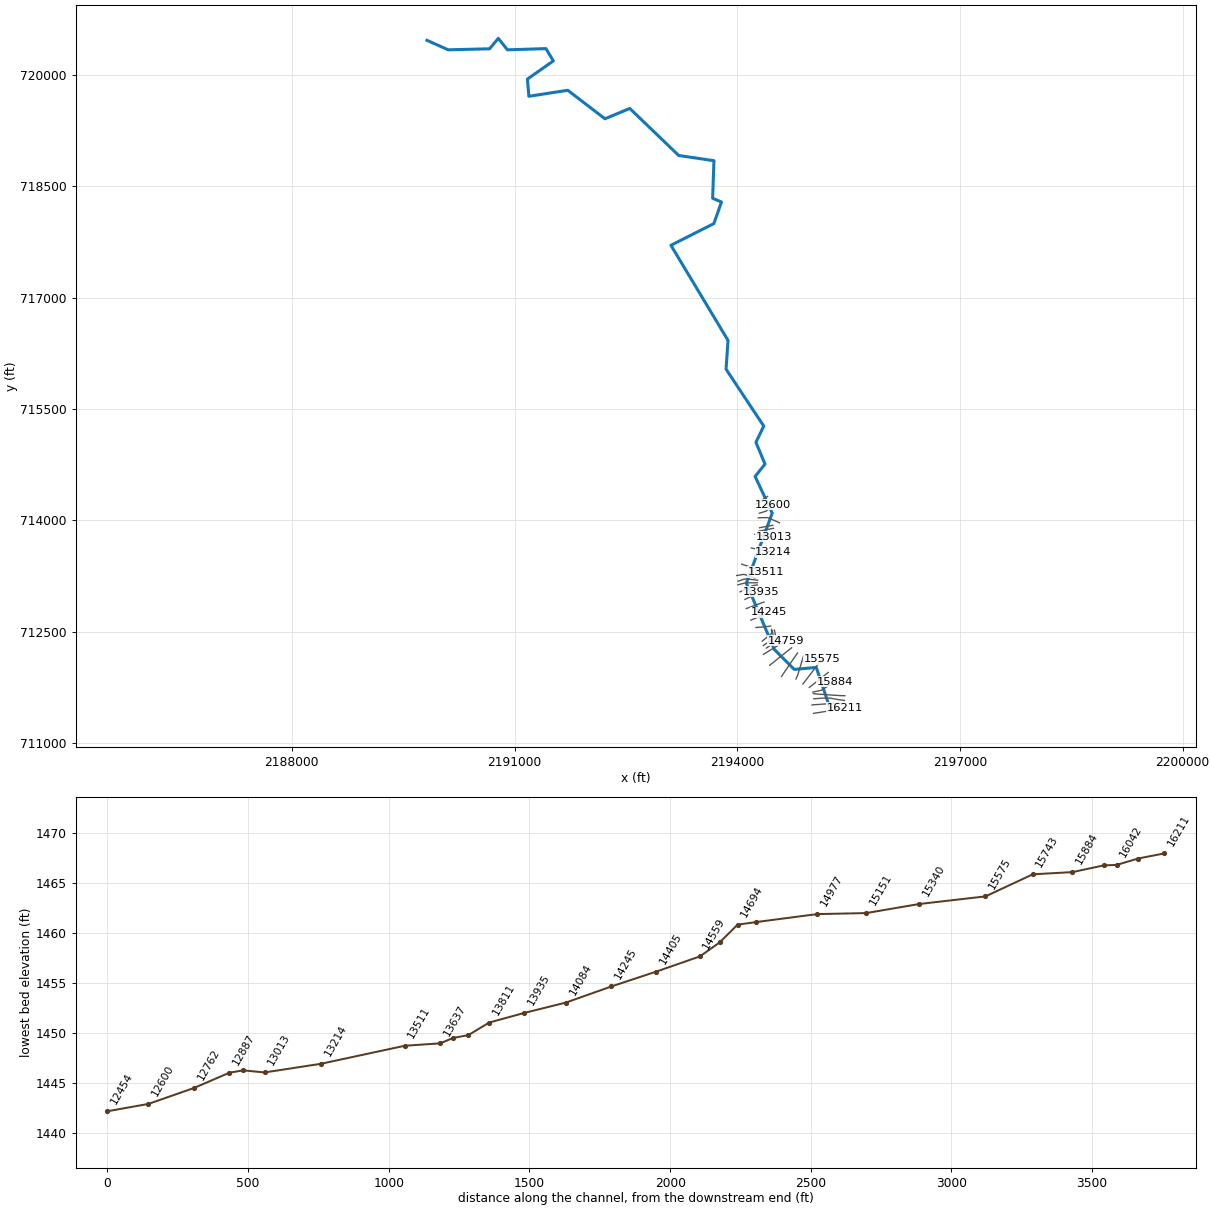
--- LISANDRN.prj (project) ---

Proj Title=LISANDRN
Current Plan=p01
Default Exp/Contr=0,0
English Units
Geom File=g01
Flow File=f01
Plan File=p01
BEGIN DESCRIPTION:
--------- MODELED AS PART OF WVEMD CTP PROGRAM, 2023----------
Stream Name: Left Fork Little Sand Run
Flood Zone:  AFH
Upshur County, WV
HEC-RAS Version: RAS 6.3
Vertical Datum: NAVD88
Projection: NAD 1983 StatePlane West Virginia S FIPS 4702 (US Feet)
Terrain: 1-meter LIDAR (FEMA Region III 3DEP collected 2016-2018)
Land Use: 2019 NLCD
Hydrologic Method:
WV SIR2010-5033 regression equations
Additional Model Notes:
None
END DESCRIPTION:
DSS Export Rating Curves= 0
DSS Export Rating Curve Sorted= 0
DSS Export Volume Flow Curves= 0
DXF OffsetX= 0
DXF OffsetY= 0
DXF ScaleX= 0
DXF ScaleY= 0

--- LISANDRN.p01 (plan) ---

Plan Title=Floodplain
Program Version=4.00
Geom File=g01
Flow File=f01
K Sum by GR=0
Std Step Tol=0.01
Critical Tol=0.01
Num of Std Step Trials=20
Max Error Tol=0.3
Flow Tol Ratio=0.001
Split Flow NTrial=30
Split Flow Tol=0.02
Split Flow Ratio=0.02
Log Output Level=0
Friction Slope Method=1
Unsteady Friction Slope Method=2
Unsteady Bridges Friction Slope Method=1
Global Log Level=0
CheckData=False
Run HTab=0
Run UNet=0
Run PostProcess=0
UNET Theta=0
UNET Theta Warmup=0
UNET ZTol=0
UNET ZSATol=0
UNET MxIter=0
UNET MaxInSteps=0
UNET DtIC=0
UNET DtMin=0
UNET MaxCRTS=0
UNET WFStab=0
UNET SFStab=0
UNET WFX=0
UNET SFX=0
UNET DSS MLevel=0
UNET DZMax Abort=0
UNET Convert EG Bridges=0
UNET Use Existing IB Tables=0
UNET Froude Limit=0
UNET Froude Power=0
Write IC File=0
Echo Input=False
Echo Output=False
Write Detailed=0

--- LISANDRN.f01 (steady flow) ---

Flow Title=Flows
Program Version=6.30
Number of Profiles= 1
Profile Names=01pct
River Rch & RM=LISANDRN,Main            ,16211
     330
River Rch & RM=LISANDRN,Main            ,14694
     414
River Rch & RM=LISANDRN,Main            ,12936
     493
River Rch & RM=LISANDRN,Main            ,9398
     569
River Rch & RM=LISANDRN,Main            ,4922
    1190
Boundary for River Rch & Prof#=LISANDRN,Main            , 1
Up Type= 0
Dn Type= 3
Dn Slope=0.0005
DSS Import GetInterval= 0
DSS Import GetPeak= 0
DSS Import FillOption= 0

--- LISANDRN.g01 (geometry) ---

Geom Title=Geometry
Program Version=6.30

River Reach=LISANDRN        ,Main
Reach XY= 30
2195260.77930771711437.589203998     2195065.355      712019.422
     2194768.832      711992.694     2194498.922      712263.377
     2194123.246      713155.121     2194471.937      714098.059
     2194241.632      714592.207     2194374.412      714758.869
     2194252.277      715051.958     2194357.815      715270.644
     2193849.931       716037.22     2193876.258      716424.944
     2193107.422      717706.071     2193685.931      717998.959
     2193788.205      718288.815     2193669.133      718340.124
     2193686.989      718846.148     2193212.358      718915.542
     2192553.179      719549.796     2192218.368      719410.549
     2191717.466      719794.552      2191193.93      719713.939
     2191173.984      719945.131     2191523.133      720190.173
     2191423.662       720355.49     2190904.303      720339.665
     2190781.939      720494.223     2190664.097      720353.258
     2190107.337      720339.608     2189820.572      720467.323

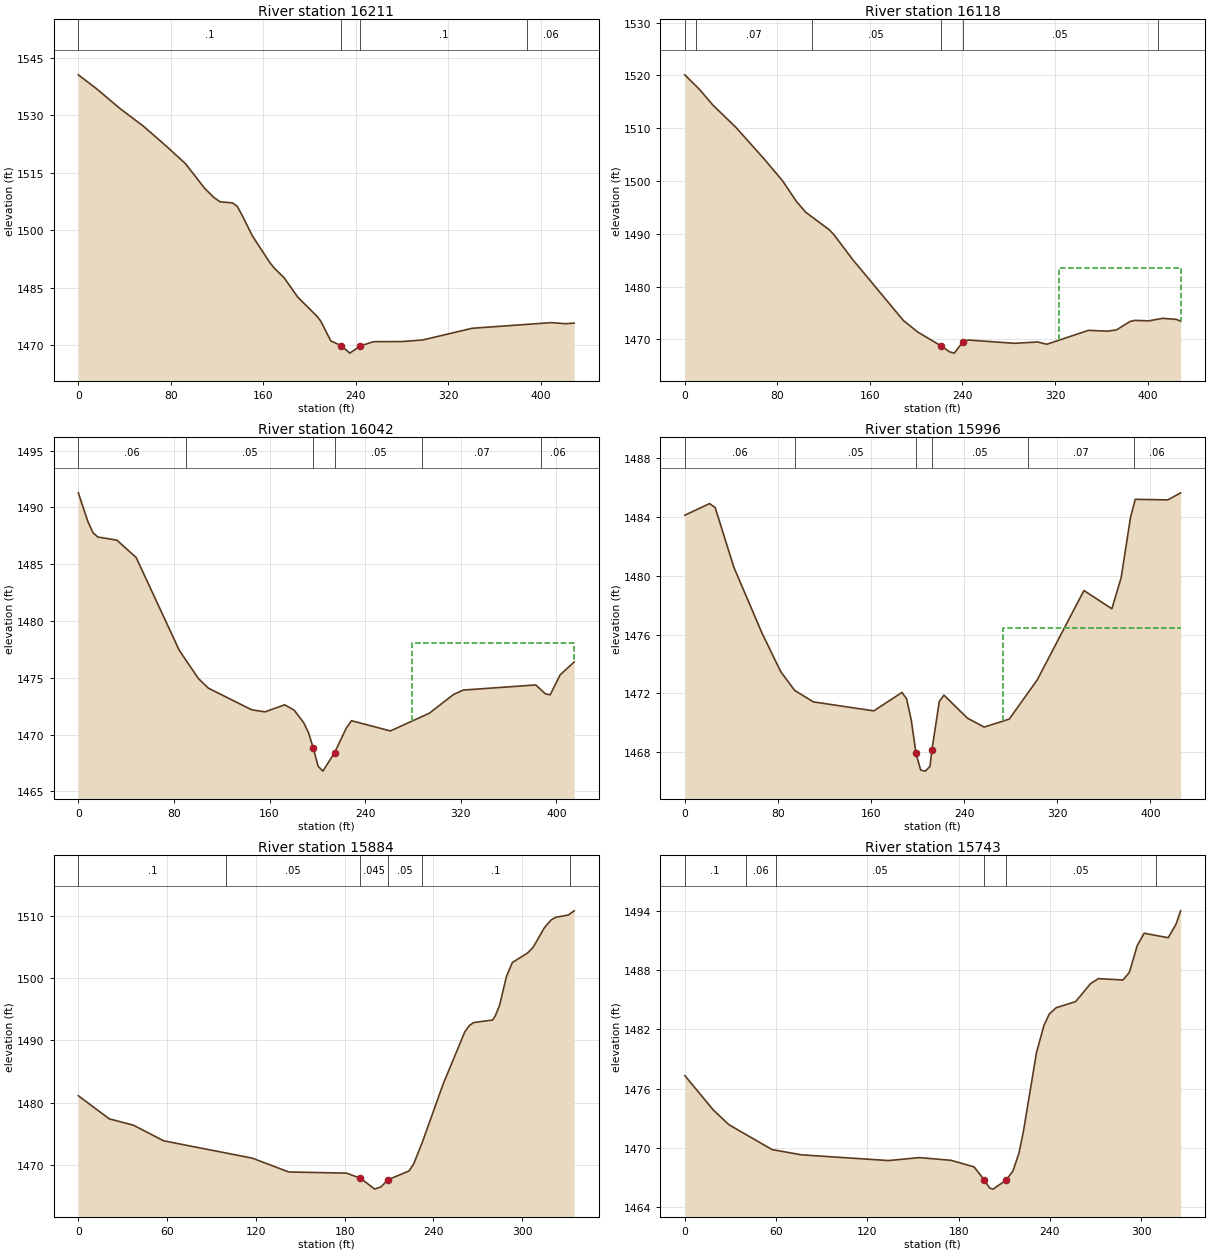
Type RM Length L Ch R = 1 ,16211   ,93.5,93.5,93.5
XS GIS Cut Line= 4
2195028.57885286711400.3521482892195229.91410539711432.592014898
2195322.02555151 711451.162870972195451.27870977711472.705064013
#Sta/Elev= 30
       0 1540.54    15.8  1536.9      36 1531.76    56.3 1527.14    76.6  1521.8
    92.8 1517.32     109 1511.03   117.1 1508.58   122.6 1507.42   133.3 1507.13
   137.3 1506.29   141.4 1504.08   150.5 1498.55   165.7 1491.54   169.7 1490.04
   177.8 1487.68     190 1482.47   206.2 1477.63   209.7 1476.29   218.4 1471.12
   227.31469.906   234.8 1467.93     2441469.794   255.2 1470.92   279.7 1470.94
     298 1471.37   340.6 1474.41   409.2 1475.89   421.7  1475.6   428.9 1475.77
#Mann= 4 ,-1,0
       0      .1       0   227.3    .045       0     244      .1       0
  387.87     .06       0
Bank Sta=227.3,244
XS Rating Curve= 0 ,0
Exp/Cntr(USF)=0,0
Exp/Cntr=0.3,0.1

Type RM Length L Ch R = 1 ,16118   ,76.4,75.9,75.3
XS GIS Cut Line= 4
2195007.80666678711514.3037816132195200.94356992711528.417632227
2195336.13940212711532.8746376852195435.67919067711536.588808899
#Sta/Elev= 30
       0  1520.1    12.4 1517.41    24.4 1514.35    44.5 1510.08    68.6 1504.17
    84.6 1500.01    96.6 1496.09   104.6 1494.07   124.7  1490.8   128.7 1489.89
   144.8 1485.22   188.9  1473.6   201.4  1471.4     221 1468.86   228.9 1467.66
   232.9 1467.42   240.1 1469.48   244.9  1469.9   284.9 1469.28   304.9 1469.53
   312.9  1469.1     349 1471.74     365 1471.57     373 1471.81     385 1473.43
     389 1473.62     401 1473.53     413 1474.01     425  1473.8428.5302 1473.47
#Mann= 6 ,-1,0
       0      .1       0      10     .07       0     110     .05       0
     221    .045       0   240.1     .05       0  408.92     .06       0
#XS Ineff= 2 , 0
                          323.66         1483.57
Permanent Ineff=
       F       F
Bank Sta=221,240.1
XS Rating Curve= 0 ,0
Exp/Cntr(USF)=0,0
Exp/Cntr=0.3,0.1

Type RM Length L Ch R = 1 ,16042   ,46.3,46,45.6
XS GIS Cut Line= 5
2195031.92868318711596.862771105 2195154.2059248711605.920344559
 2195259.5002162711604.7881478772195356.86913083 711586.67300097
2195444.04827532711575.351034153
#Sta/Elev= 30
       0 1491.29       8 1488.76    12.3 1487.77    16.3  1487.4    32.3 1487.12
    48.4 1485.59    84.5 1477.41   100.5 1474.93   108.8 1474.09   145.1 1472.18
   156.2    1472   172.6 1472.62   180.5 1472.16   188.6 1471.04   192.6 1470.16
   196.6 1468.81   200.6 1467.22   204.6 1466.78   214.41468.402   224.2 1470.57
   228.6 1471.22   261.1 1470.32   293.7 1471.88   313.9 1473.53   322.2 1473.92
   382.7 1474.37   390.8 1473.59   394.8  1473.5   403.2 1475.27414.8636 1476.39
#Mann= 6 ,-1,0
       0     .06       0      90     .05       0   196.6    .045       0
   214.4     .05       0  287.91     .07       0  386.95     .06       0
#XS Ineff= 2 , 0
                          278.87         1478.04
Permanent Ineff=
       F       F
Bank Sta=196.6,214.4
XS Rating Curve= 0 ,0
Exp/Cntr(USF)=0,0
Exp/Cntr=0.3,0.1

Type RM Length L Ch R = 1 ,15996   ,103.1,111.5,119.2
XS GIS Cut Line= 4
2195026.26769977 711667.058965372195080.61314049 711660.26578528
2195401.02480141711638.7540483282195451.20489747711638.255272918
#Sta/Elev= 30
       0  1484.1    21.3 1484.89    26.1 1484.62    42.2 1480.56    66.4 1476.09
    82.4 1473.49    94.4 1472.21   110.5 1471.43   162.4 1470.82   186.6 1472.07
   190.6 1471.64   194.6  1470.2   198.7 1467.93   202.7  1466.8   206.7 1466.73
   210.7 1467.05   212.41468.175   218.7 1471.46   222.7 1471.89   242.8 1470.33
   257.3 1469.72   278.8 1470.26   302.9 1472.93     343 1478.99     367 1477.75
     375 1479.87   383.1 1483.99   387.1 1485.18   415.1 1485.14426.0839 1485.62
#Mann= 6 ,-1,0
       0     .06       0   94.77     .05       0   198.7    .045       0
   212.4     .05       0  294.77     .07       0   385.9     .06       0
#XS Ineff= 2 , 0
                          273.24         1476.46
Permanent Ineff=
       F       F
Bank Sta=198.7,212.4
XS Rating Curve= 0 ,0
Exp/Cntr(USF)=0,0
Exp/Cntr=0.3,0.1

Type RM Length L Ch R = 1 ,15884   ,139.3,140.8,142.2
XS GIS Cut Line= 3
2195019.69201466  711687.38416022195129.63148261711710.412021729
2195319.05421454711827.779832102
#Sta/Elev= 30
       0  1481.1    20.9 1477.38    37.3 1476.35    57.7 1473.84   117.6 1471.05
   142.3 1468.82   181.2 1468.64   190.6 1467.83   200.4 1466.06   204.7 1466.44
   209.2 1467.56   223.5 1468.98   226.6 1470.07   232.4 1473.53   246.7 1483.04
   261.2 1491.37   264.4 1492.43   267.3 1492.89     280 1493.29   281.8 1493.94
   284.7 1495.63   289.4 1500.31   293.4 1502.56   303.5 1504.06   307.4 1504.99
     315 1508.14   319.6 1509.41   322.6 1509.83   331.2  1510.2335.1619 1510.88
#Mann= 6 ,-1,0
       0      .1       0     100     .05       0   190.6    .045       0
   209.2     .05       0  232.33      .1       0  332.33     .06       0
Bank Sta=190.6,209.2
XS Rating Curve= 0 ,0
Exp/Cntr(USF)=0,0
Exp/Cntr=0.3,0.1

Type RM Length L Ch R = 1 ,15743   ,165.6,168.2,171.3
XS GIS Cut Line= 2
2194971.18493861711749.485102904 2195226.5713513711952.056000933
#Sta/Elev= 30
       0 1477.33    18.8 1473.84      29 1472.36    57.4 1469.84    76.7 1469.31
     134 1468.73   154.2 1469.03   174.9 1468.76   190.2 1468.09   196.9 1466.76
   200.4 1465.95   202.6 1465.84   211.2 1466.74   215.7 1467.66   219.7 1469.49
   222.6 1471.66   231.2 1479.64   236.1  1482.4   239.6 1483.55   244.1 1484.19
     257 1484.82   266.8 1486.64   271.9 1487.14   288.1    1487   292.3 1487.78
   297.4 1490.47     302 1491.73   317.8 1491.28   322.9 1492.63325.9712    1494
#Mann= 6 ,-1,0
       0      .1       0      40     .06       0      60     .05       0
   196.9    .045       0   211.2     .05       0     310     .06       0
Bank Sta=196.9,211.2
XS Rating Curve= 0 ,0
Exp/Cntr(USF)=0,0
Exp/Cntr=0.3,0.1

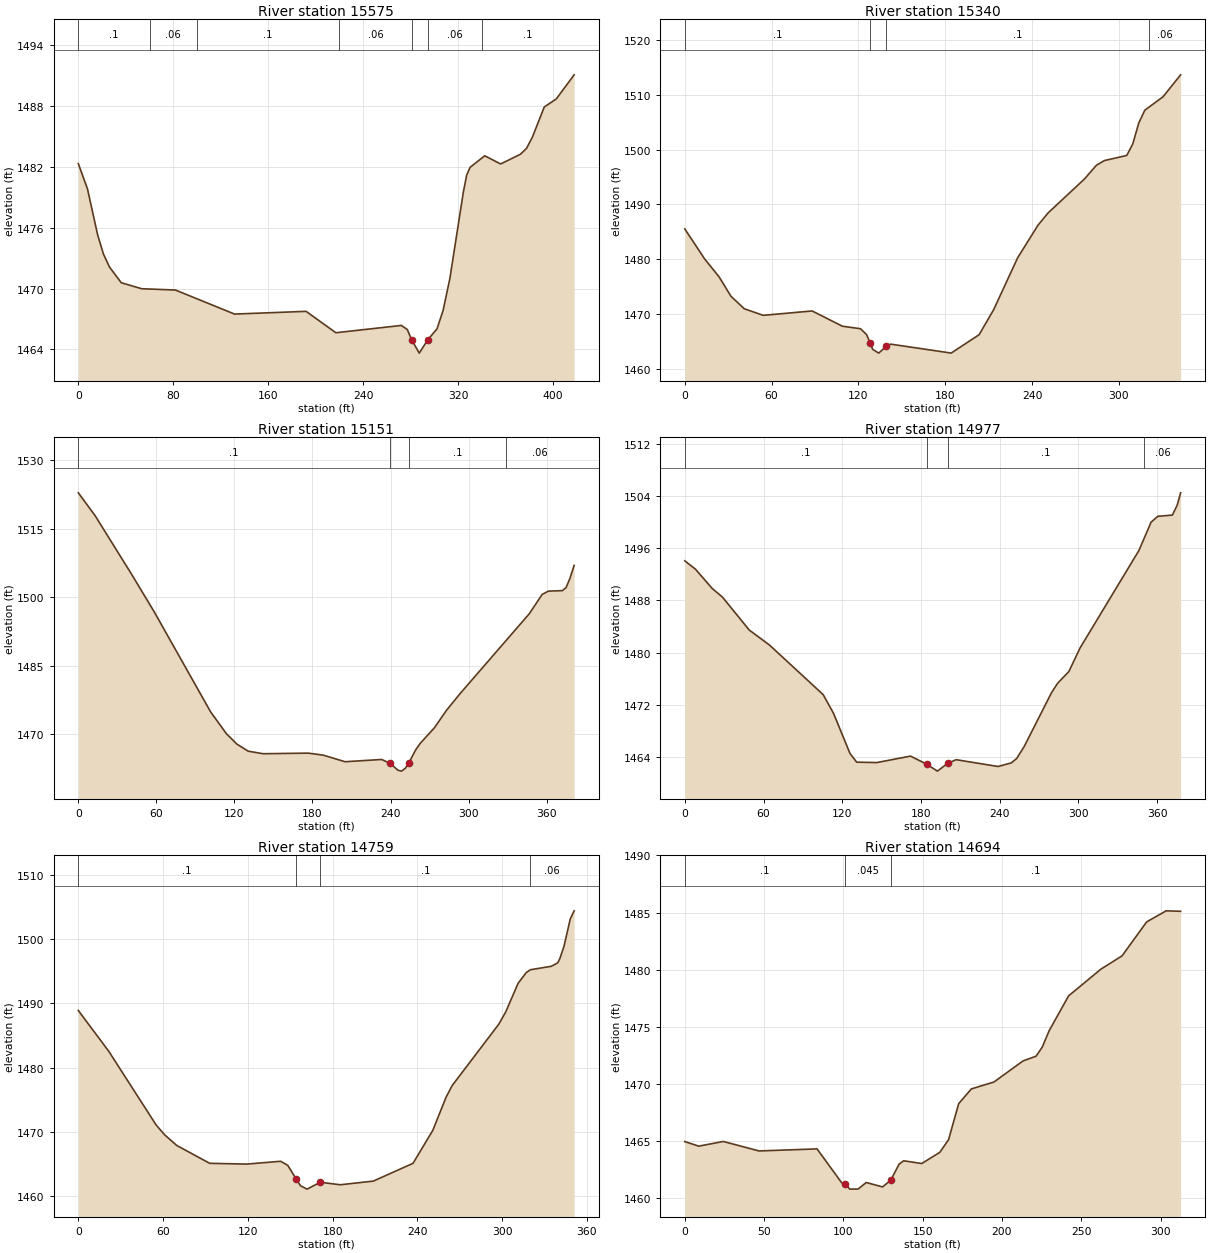
Type RM Length L Ch R = 1 ,15575   ,231.2,235.3,240.6
XS GIS Cut Line= 2
2194886.27898465711796.2836602042195138.99119407712129.221967856
#Sta/Elev= 30
       0 1482.31     7.7 1479.83    16.3 1475.28    21.2 1473.39    26.2 1472.13
    36.2 1470.57    53.4 1469.98    81.9 1469.85   131.7 1467.48     192 1467.75
   217.1 1465.64   272.3 1466.36   277.3 1465.96     281 1464.95   287.4 1463.63
   294.71464.961   302.4 1466.03   307.5 1467.84   313.2 1470.98   324.6 1479.52
   327.4 1481.19   330.3 1481.95   342.6 1483.09     356 1482.28   372.7 1483.24
   377.8 1483.81   382.8 1484.93   392.8  1487.9   402.9 1488.69417.9849 1491.07
#Mann= 7 ,-1,0
       0      .1       0      60     .06       0     100      .1       0
     220     .06       0     281    .045       0   294.7     .06       0
     340      .1       0
Bank Sta=281,294.7
XS Rating Curve= 0 ,0
Exp/Cntr(USF)=0,0
Exp/Cntr=0.3,0.1

Type RM Length L Ch R = 1 ,15340   ,190.2,189,184.5
XS GIS Cut Line= 3
2194791.73847056711863.5250158682194816.25200057711919.237584083
2194898.21444796 712188.83632847
#Sta/Elev= 30
       0 1485.52    13.7 1480.05    23.7 1476.78    31.9 1473.24    41.1 1470.96
    54.2 1469.76      88 1470.56   108.9 1467.78   121.4 1467.32   125.6 1466.26
     128  1464.8   129.8 1463.58     134 1462.87   139.3 1464.14   142.3 1464.51
   184.1 1462.88   203.4 1466.23   213.4 1470.77   230.1 1480.29   244.1  1486.2
     251 1488.42   276.1  1494.6   284.5 1497.14     290 1497.99   305.4 1498.91
   309.6 1501.03   313.7 1504.81   317.9 1507.17   330.5 1509.62342.6495 1513.62
#Mann= 4 ,-1,0
       0      .1       0     128    .045       0   139.3      .1       0
  320.87     .06       0
Bank Sta=128,139.3
XS Rating Curve= 0 ,0
Exp/Cntr(USF)=0,0
Exp/Cntr=0.3,0.1

Type RM Length L Ch R = 1 ,15151   ,176.5,173.6,168.7
XS GIS Cut Line= 3
2194597.85873317711898.4382252832194691.45584777712038.833897184
2194812.53782936712213.399944257
#Sta/Elev= 30
       0 1522.91    12.9 1517.91    41.1 1505.01    58.5 1496.77   101.7 1474.94
   113.9 1470.14   121.9 1467.88   130.6 1466.33   142.1 1465.77   176.7  1465.9
   188.2 1465.47   205.1 1464.02   233.2 1464.51   239.7 1463.67   245.7 1462.16
   248.5 1461.96   251.4 1462.59   254.2  1463.8   259.2 1466.54   262.9 1468.06
   273.8 1471.46     283 1475.26   293.3 1478.87   346.8 1496.46   356.6 1500.66
   361.4 1501.38   372.1 1501.49     375 1502.16   377.9 1504.13   381.2 1507.02
#Mann= 4 ,-1,0
       0      .1       0   239.7    .045       0   254.2      .1       0
  328.73     .06       0
Bank Sta=239.7,254.2
XS Rating Curve= 0 ,0
Exp/Cntr(USF)=0,0
Exp/Cntr=0.3,0.1

Type RM Length L Ch R = 1 ,14977   ,216,218,211.7
XS GIS Cut Line= 2
2194437.77336844712048.1514229962194733.05456537712283.969197329
#Sta/Elev= 30
       0 1494.05     8.1 1492.78    20.9 1489.82    28.7  1488.5    49.1 1483.46
    64.5 1481.17   105.5 1473.56   113.4 1470.69   125.9 1464.57     131 1463.23
   146.4 1463.17     172 1464.16   184.6  1462.9   192.5 1461.86   200.4 1463.06
   206.8 1463.61   238.8 1462.57   248.8 1463.12   252.9 1463.78   258.6  1465.6
   279.5 1473.87   284.2 1475.32   292.7  1477.1   301.3 1480.73   346.1 1495.63
   355.4 1499.98   360.6 1500.87   371.6 1501.05   375.3 1502.59377.8902 1504.46
#Mann= 4 ,-1,0
       0      .1       0   184.6    .045       0   200.4      .1       0
     350     .06       0
Bank Sta=184.6,200.4
XS Rating Curve= 0 ,0
Exp/Cntr(USF)=0,0
Exp/Cntr=0.3,0.1

Type RM Length L Ch R = 1 ,14759   ,63.6,65.6,76.6
XS GIS Cut Line= 3
2194353.83309899712195.7553382912194632.62520989712365.415011044
2194654.63511339 712376.41996279
#Sta/Elev= 30
       0 1488.89    21.5 1482.55    55.1 1471.05      61 1469.54    69.7 1467.86
      93 1465.08   119.2 1464.96   143.2  1465.4   148.3 1464.75   154.1 1462.67
   157.3 1461.58   161.9 1461.06   171.3 1462.13   185.4 1461.74   208.8 1462.31
   236.9 1465.08   250.9 1470.21   260.3 1475.38   264.7 1477.22   297.7 1486.78
   302.6  1488.7   311.3 1493.13   317.1 1494.81     320 1495.24   334.8 1495.78
   339.3 1496.31   340.8 1496.95   343.8 1498.91   348.2 1503.15350.9657 1504.42
#Mann= 4 ,-1,0
       0      .1       0   154.1    .045       0   171.3      .1       0
     320     .06       0
Bank Sta=154.1,171.3
XS Rating Curve= 0 ,0
Exp/Cntr(USF)=0,0
Exp/Cntr=0.3,0.1

Type RM Length L Ch R = 1 ,14694   ,62,63.1,47.2
XS GIS Cut Line= 6
2194392.06433193712280.2646135562194445.71347169712316.580954318
2194508.44169664712367.7539799372194529.07598117712385.086778938
2194525.77449564712410.6732917472194501.01335421712522.098428177
#Sta/Elev= 30
       0 1464.96     8.8 1464.56    24.3 1464.97    46.8 1464.14    83.4 1464.32
    98.9 1461.36   101.1 1461.23   104.1  1460.8   109.3 1460.81   114.4 1461.38
   124.7 1460.99   129.9 1461.59   135.1 1462.98     138 1463.28   149.4 1463.04
   160.8 1464.02   166.3 1465.12   172.7 1468.28   180.7 1469.57   194.9 1470.17
   213.3 1472.02   221.5 1472.43   225.4 1473.23   229.7 1474.65     242 1477.71
   262.5 1480.06   275.7 1481.21   291.2 1484.18   303.5 1485.15312.6288 1485.11
#Mann= 3 ,-1,0
       0      .1       0   101.1    .045       0   129.9      .1       0
Bank Sta=101.1,129.9
XS Rating Curve= 0 ,0
Exp/Cntr(USF)=0,0
Exp/Cntr=0.3,0.1

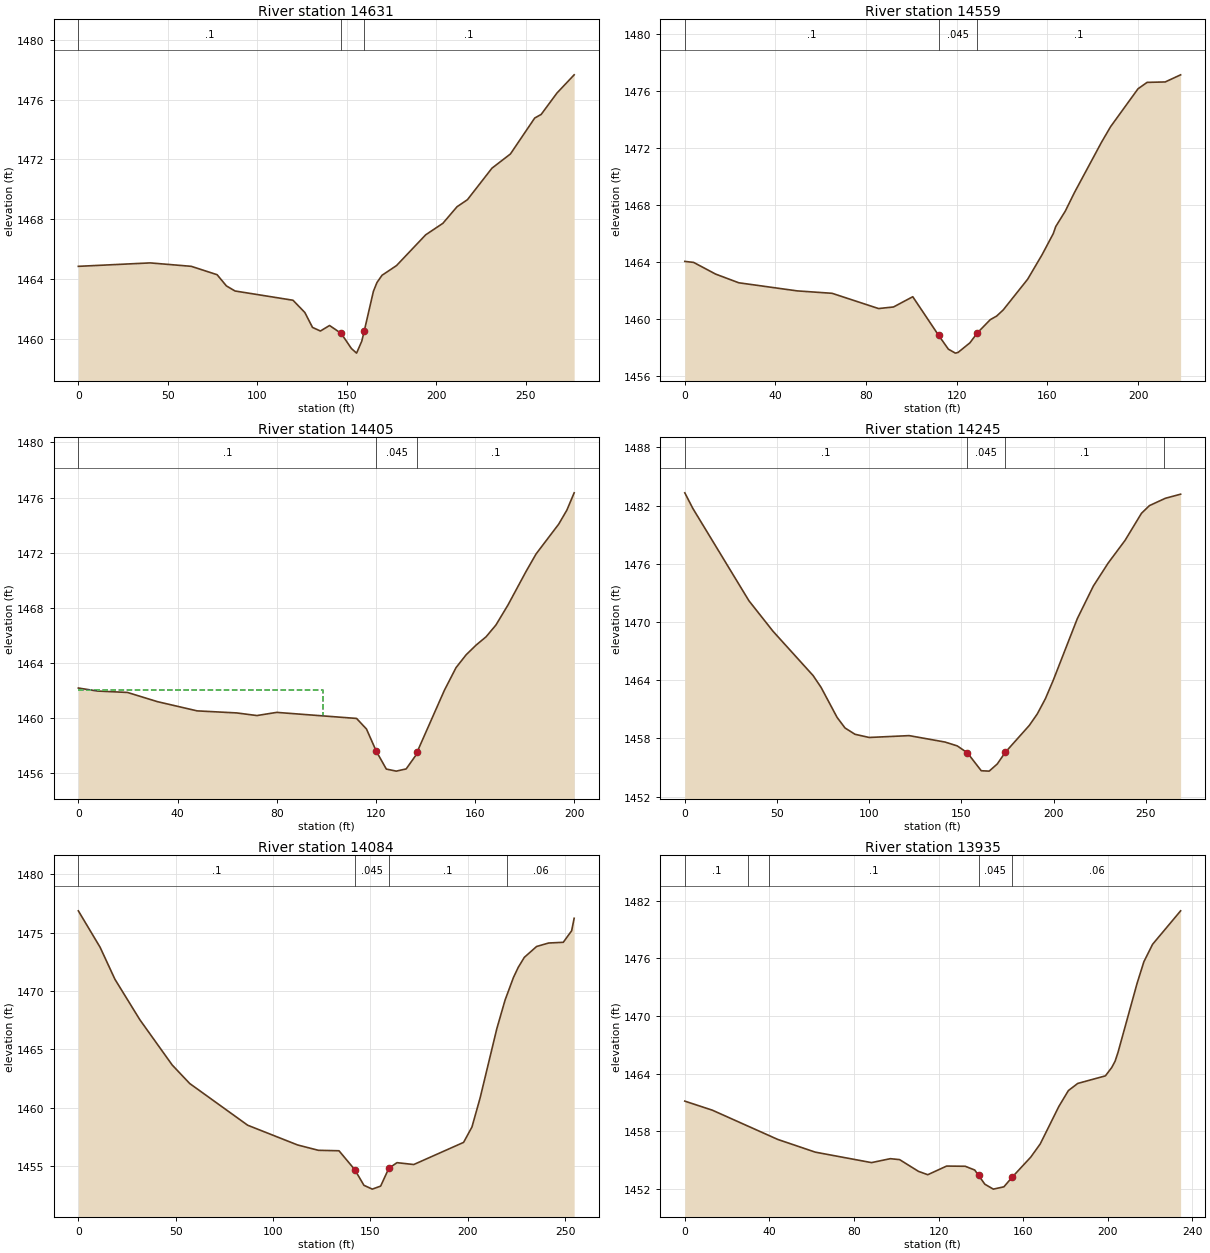
Type RM Length L Ch R = 1 ,14631   ,69.3,71,70.5
XS GIS Cut Line= 5
2194351.62113426712314.1048401752194455.61792826712384.261407557
2194473.77609864 712395.816606892194491.93426902712409.022548985
2194472.12535588712514.670085748
#Sta/Elev= 30
       0 1464.84    40.1 1465.07    63.1 1464.84    77.5 1464.28    82.7 1463.53
    87.5 1463.19   119.9 1462.57   126.5 1461.75   130.8 1460.75   135.2 1460.51
   140.3 1460.88   146.8 1460.35   152.5 1459.34   155.4 1459.03   158.3 1459.83
   159.7 1460.52   164.8 1463.17   166.8 1463.76   169.6 1464.24   177.7 1464.89
     194 1466.95   203.6 1467.72   211.5 1468.83   217.3  1469.3     231 1471.41
   241.3 1472.36   254.9 1474.77   258.5 1475.01   267.3 1476.44276.9125 1477.66
#Mann= 3 ,-1,0
       0      .1       0   146.8    .045       0   159.7      .1       0
Bank Sta=146.8,159.7
XS Rating Curve= 0 ,0
Exp/Cntr(USF)=0,0
Exp/Cntr=0.3,0.1

Type RM Length L Ch R = 1 ,14559   ,160.4,154.6,144.1
XS GIS Cut Line= 3
2194337.58607661712374.257467128  2194465.060101712476.970350092
2194462.30886307712531.995108823
#Sta/Elev= 30
       0 1464.06     3.9 1463.99    13.6 1463.17    23.8 1462.56    49.6 1461.99
      65 1461.82    85.5 1460.75    92.1 1460.86   100.6 1461.58     112 1458.87
   116.3  1457.9   119.4 1457.62   120.6 1457.67   125.8 1458.34   129.1 1459.04
   134.8 1459.97   137.6 1460.22   140.5 1460.65   151.3 1462.81   157.7 1464.54
   162.6 1466.01   163.7 1466.51   167.9 1467.59   171.9 1468.88   183.9 1472.43
   187.9 1473.52     200 1476.18     204 1476.63     212 1476.66218.7992 1477.16
#Mann= 3 ,-1,0
       0      .1       0     112    .045       0   129.1      .1       0
Bank Sta=112,129.1
XS Rating Curve= 0 ,0
Exp/Cntr(USF)=0,0
Exp/Cntr=0.3,0.1

Type RM Length L Ch R = 1 ,14405   ,155.7,159.8,164.2
XS GIS Cut Line= 4
2194252.39959828 712557.367636462194322.70901221712562.462521527
2194428.68262162712572.6522916632194451.10011592 712577.74717673
#Sta/Elev= 28
       0 1462.15     7.8 1461.93    19.8 1461.83    31.9 1461.16    47.9 1460.49
    63.9 1460.34      72 1460.15      80 1460.38   112.2 1459.94   116.2 1459.17
   120.2 1457.54   124.2 1456.26   128.2 1456.11   132.2 1456.27   136.3 1457.31
   136.6 1457.49   147.6 1461.98   152.3 1463.63   156.4 1464.57   160.4 1465.27
   164.4 1465.87   168.4 1466.73   173.3  1468.2   180.5 1470.61   184.6  1471.9
   193.7 1474.06     197 1475.08199.9453 1476.34
#Mann= 3 ,-1,0
       0      .1       0   120.2    .045       0   136.6      .1       0
#XS Ineff= 2 , 0
        98.59314    1462
Permanent Ineff=
       T       F
Bank Sta=120.2,136.6
XS Rating Curve= 0 ,0
Exp/Cntr(USF)=0,0
Exp/Cntr=0.3,0.1

Type RM Length L Ch R = 1 ,14245   ,161.8,161.3,160.7
XS GIS Cut Line= 2
2194184.12813837712656.2084067722194431.73955266712761.163039166
#Sta/Elev= 30
       0 1483.31     4.4 1481.69    34.8 1472.18    47.8 1469.05    69.6 1464.47
    73.9 1463.26    82.6 1460.16    86.9 1459.07    92.3 1458.42     100 1458.09
   121.7 1458.28   141.1 1457.62   147.8 1457.22   153.3  1456.5   160.8 1454.66
   165.1 1454.62   169.5 1455.36   173.8 1456.55   186.9 1459.34   191.2 1460.52
   195.6 1462.09   199.9 1464.01   212.9 1470.34   221.6  1473.7   229.6 1476.06
   238.8 1478.41   247.7  1481.2     252 1481.99   260.7 1482.75268.9366 1483.17
#Mann= 4 ,-1,0
       0      .1       0   153.3    .045       0   173.8      .1       0
     260     .06       0
Bank Sta=153.3,173.8
XS Rating Curve= 0 ,0
Exp/Cntr(USF)=0,0
Exp/Cntr=0.3,0.1

Type RM Length L Ch R = 1 ,14084   ,146.4,148.7,148.3
XS GIS Cut Line= 2
2194122.53663889712812.4515488472194361.43013873 712900.76289002
#Sta/Elev= 30
       0 1476.88    11.2 1473.75    18.8 1471.01    31.6 1467.54    48.2 1463.66
    57.2 1462.07      87 1458.49   112.6  1456.8   123.3 1456.34   133.9  1456.3
     142 1454.68   146.7 1453.34     151 1453.01   155.3 1453.27   159.5  1454.8
   163.7 1455.28   172.3 1455.12   197.9 1457.02   202.2 1458.34   206.4 1460.84
     215 1466.79   219.2 1469.22   223.5 1471.16     226 1472.04   229.1 1472.89
   235.4 1473.82   241.6 1474.12   249.1 1474.18   253.4 1475.17254.6939 1476.24
#Mann= 4 ,-1,0
       0      .1       0     142    .045       0   159.5      .1       0
     220     .06       0
Bank Sta=142,159.5
XS Rating Curve= 0 ,0
Exp/Cntr(USF)=0,0
Exp/Cntr=0.3,0.1

Type RM Length L Ch R = 1 ,13935   ,123.6,124.3,124.2
XS GIS Cut Line= 2
2194104.42149198712935.8609871532194316.14227146713036.626491824
#Sta/Elev= 30
       0 1461.13      13 1460.19      44 1457.14    61.7 1455.82    88.3 1454.73
    97.2 1455.14   101.6 1455.04   110.5 1453.82   114.9 1453.47   123.8 1454.37
   132.6 1454.35   137.1 1453.96   138.9 1453.41   141.9 1452.48   145.9 1451.97
   150.9 1452.21   154.8 1453.21   163.6  1455.3   168.1 1456.68   176.9 1460.58
   181.4 1462.23   185.8 1462.97   198.9 1463.76   201.9 1464.63   203.5 1465.29
   204.9 1466.23   213.9  1473.4   217.1 1475.64   221.2 1477.45234.4768 1480.94
#Mann= 5 ,-1,0
       0      .1       0      30     .08       0      40      .1       0
   138.9    .045       0   154.8     .06       0
Bank Sta=138.9,154.8
XS Rating Curve= 0 ,0
Exp/Cntr(USF)=0,0
Exp/Cntr=0.3,0.1

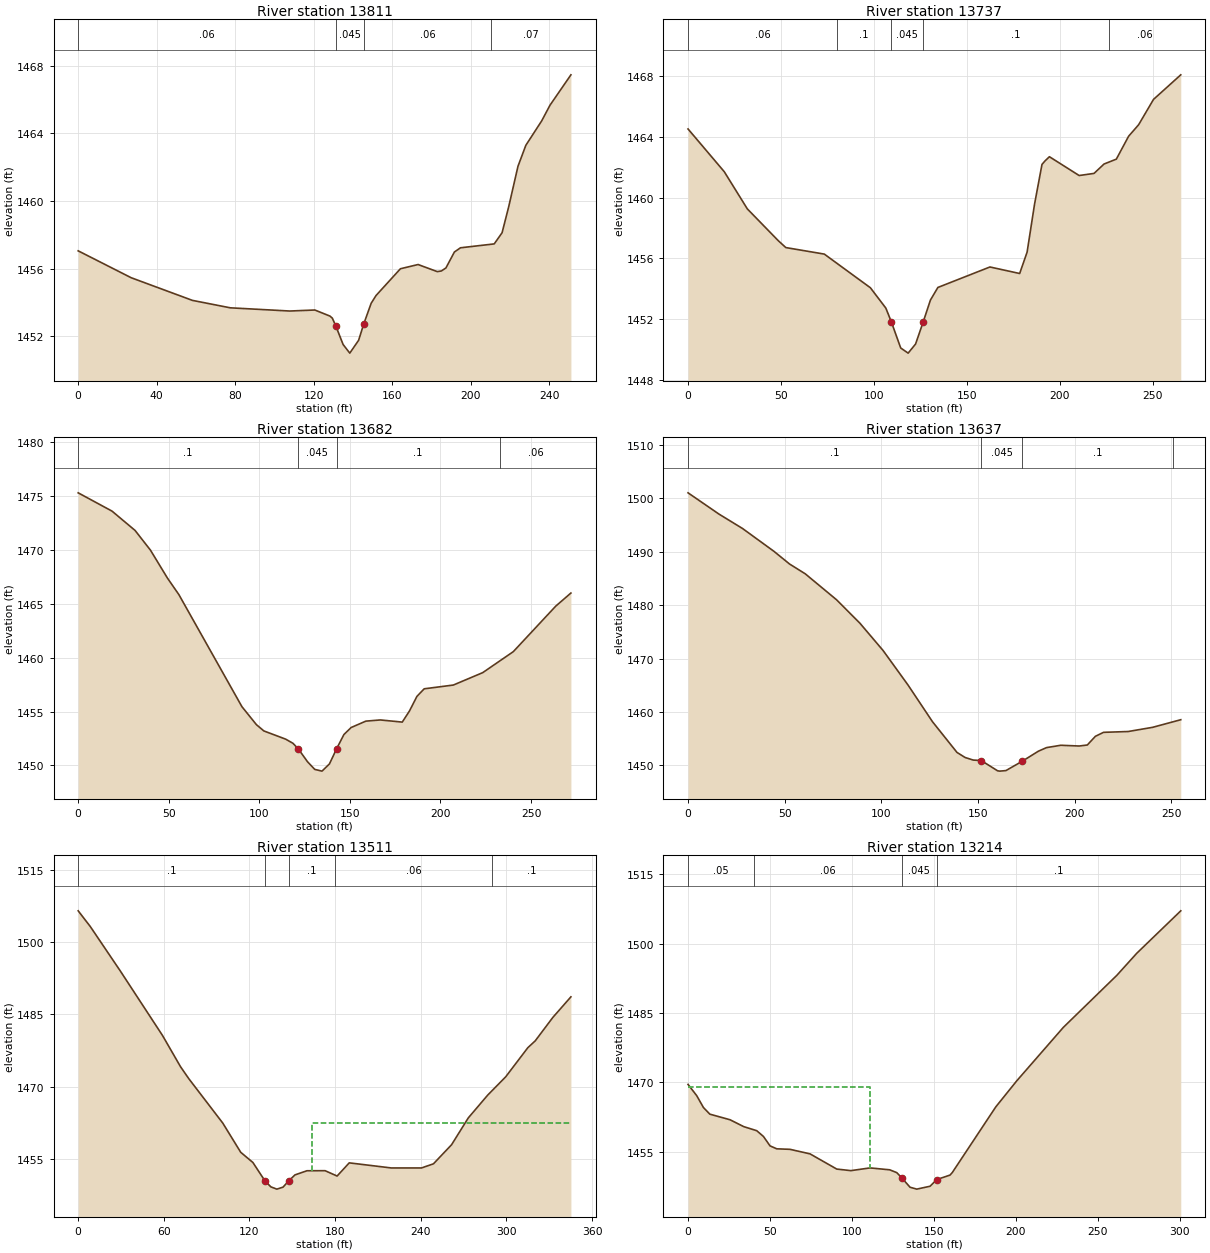
Type RM Length L Ch R = 1 ,13811   ,79.2,74.1,67.2
XS GIS Cut Line= 3
2194039.88628112713037.7586885062194210.84798006713121.541242952
2194270.85440419713130.598816405
#Sta/Elev= 30
       0 1457.06      27 1455.47    58.2 1454.13    77.5 1453.69   107.8  1453.5
   120.6 1453.56   128.3  1453.2   129.5 1453.08   131.3 1452.61     135 1451.52
   138.4 1451.01   142.9 1451.77   145.51452.732   149.3 1453.96   151.8 1454.42
   164.2    1456   173.2 1456.25     183 1455.83   185.1 1455.87   187.4 1456.05
   191.7 1456.99   194.8 1457.24     212 1457.47     216 1458.13   219.4 1459.68
   224.1 1462.06   228.1  1463.3   236.2 1464.75   240.4 1465.67251.0737 1467.47
#Mann= 4 ,-1,0
       0     .06       0   131.3    .045       0   145.5     .06       0
  210.39     .07       0
Bank Sta=131.3,145.5
XS Rating Curve= 0 ,0
Exp/Cntr(USF)=0,0
Exp/Cntr=0.3,0.1

Type RM Length L Ch R = 1 ,13737   ,54.7,54.4,52.6
XS GIS Cut Line= 3
2194009.31697072713131.7310130872194112.34686875713158.903733448
2194270.85440419 713160.03593013
#Sta/Elev= 30
       0 1464.53    19.5 1461.71    31.9 1459.26    48.5 1457.17    52.6 1456.71
    73.3 1456.28    98.1 1454.06   106.4 1452.72   109.31451.835   114.4 1450.09
   118.4 1449.75   122.4 1450.35   126.4 1451.77   130.4 1453.25   134.4 1454.08
   162.4 1455.43   178.4    1455   182.4 1456.41   186.4 1459.57   190.4 1462.19
     192 1462.42   194.4  1462.7   210.4 1461.46   218.4  1461.6   223.8 1462.22
   230.4 1462.54     237 1464.05   242.4 1464.81   250.4 1466.48265.0645  1468.1
#Mann= 5 ,-1,0
       0     .06       0      80      .1       0   109.3    .045       0
   126.4      .1       0  226.55     .06       0
Bank Sta=109.3,126.4
XS Rating Curve= 0 ,0
Exp/Cntr(USF)=0,0
Exp/Cntr=0.3,0.1

Type RM Length L Ch R = 1 ,13682   ,49.6,45.5,42.2
XS GIS Cut Line= 5
 2194010.4491674  713180.41547042194094.23172184713208.720387443
2194125.93322893713212.1169774882194178.01427629713206.455994079
 2194276.5153876713194.001830581
#Sta/Elev= 30
       0  1475.3    18.7  1473.6    31.4 1471.81    39.9 1469.98    49.3 1467.38
    55.6 1465.85    90.4 1455.45    98.4 1453.78   102.5  1453.2   114.5 1452.44
   118.5 1452.06   121.4 1451.56   126.6 1450.34   130.6 1449.63   134.6 1449.47
   138.7 1450.14   142.7 1451.56   146.7 1452.87   150.7 1453.52   158.8 1454.11
   166.8 1454.22   178.9 1454.02   182.9 1455.06     187 1456.41     191 1457.11
   207.1 1457.46   223.3 1458.61   240.2 1460.56   263.6 1464.78271.9907    1466
#Mann= 4 ,-1,0
       0      .1       0   121.4    .045       0   142.7      .1       0
  232.71     .06       0
Bank Sta=121.4,142.7
XS Rating Curve= 0 ,0
Exp/Cntr(USF)=0,0
Exp/Cntr=0.3,0.1

Type RM Length L Ch R = 1 ,13637   ,125,125.9,124.5
XS GIS Cut Line= 3
2193992.33402049713257.4048447562194091.96732848  713273.2555983
2194238.02070042713224.571140987
#Sta/Elev= 30
       0 1501.01      16 1497.03    28.2 1494.33    44.4 1490.07    52.5 1487.69
    60.6 1485.86    76.8    1481    88.9 1476.61   100.9 1471.49   113.8 1465.03
   126.4 1458.19   139.1 1452.43   143.3 1451.48   147.5    1451   151.7 1450.91
   151.7  1450.9   160.1 1448.99   161.2 1448.93   164.4 1449.03   172.8 1450.77
   181.2 1452.66   185.4 1453.33   192.8 1453.77   202.3 1453.63   206.5 1453.82
   210.7 1455.45   214.9 1456.19   227.6 1456.34   240.2 1457.12254.8401 1458.55
#Mann= 4 ,-1,0
       0      .1       0   151.7    .045       0   172.8      .1       0
  250.89     .06       0
Bank Sta=151.7,172.8
XS Rating Curve= 0 ,0
Exp/Cntr(USF)=0,0
Exp/Cntr=0.3,0.1

Type RM Length L Ch R = 1 ,13511   ,293.1,297.5,298.5
XS GIS Cut Line= 3
2194060.14002176713411.1319942052194345.70518481713315.524274417
2194388.39727403713304.623650785
#Sta/Elev= 30
       0 1506.54     8.5 1503.27    29.6    1494    59.1 1480.62    71.7 1474.14
    77.4 1471.69   101.3 1462.42   113.9 1456.34   122.4 1454.23   130.8 1450.43
     135 1449.16   139.2 1448.69   143.5  1449.1   147.7 1450.46   151.9 1451.65
   160.3 1452.51     173 1452.52   181.4 1451.41   189.9 1454.15   219.4 1453.09
   240.5 1453.09   248.9 1453.95   261.6 1457.92   273.3 1463.49   286.9 1468.23
   299.5 1472.03     315 1478.08   320.2 1479.51   332.6  1484.4345.2067 1488.66
#Mann= 5 ,-1,0
       0      .1       0   130.8    .045       0   147.7      .1       0
     180     .06       0     290      .1       0
#XS Ineff= 2 , 0
                          163.66         1462.51
Permanent Ineff=
       F       T
Bank Sta=130.8,147.7
XS Rating Curve= 0 ,0
Exp/Cntr(USF)=0,0
Exp/Cntr=0.3,0.1

Type RM Length L Ch R = 1 ,13214   ,198.5,200.8,201.9
XS GIS Cut Line= 2
2194190.97163831713627.5073600412194486.60077187713573.413518582
#Sta/Elev= 30
       0 1469.55     5.3 1467.11     9.4 1464.54    13.3 1463.11    25.6  1461.9
      34 1460.41    41.9 1459.53      46 1458.28      50 1456.25    54.1 1455.61
    62.2  1455.5    74.4 1454.52    90.7 1451.23    99.3 1450.89     111 1451.48
     123 1451.07   127.3 1450.46   130.2  1449.4   135.4  1447.3   139.5 1446.89
   147.6 1447.51   151.7 1448.96   159.8 1449.93   161.2 1450.49   187.7 1464.68
   200.5 1470.32   228.9 1481.88   261.5 1493.13   273.7 1497.92300.5374  1507.1
#Mann= 4 ,-1,0
       0     .05       0      40     .06       0   130.2    .045       0
   151.7      .1       0
#XS Ineff= 2 , 0
        110.7397 1469.09
Permanent Ineff=
       T       F
Bank Sta=130.2,151.7
XS Rating Curve= 0 ,0
Exp/Cntr(USF)=0,0
Exp/Cntr=0.3,0.1

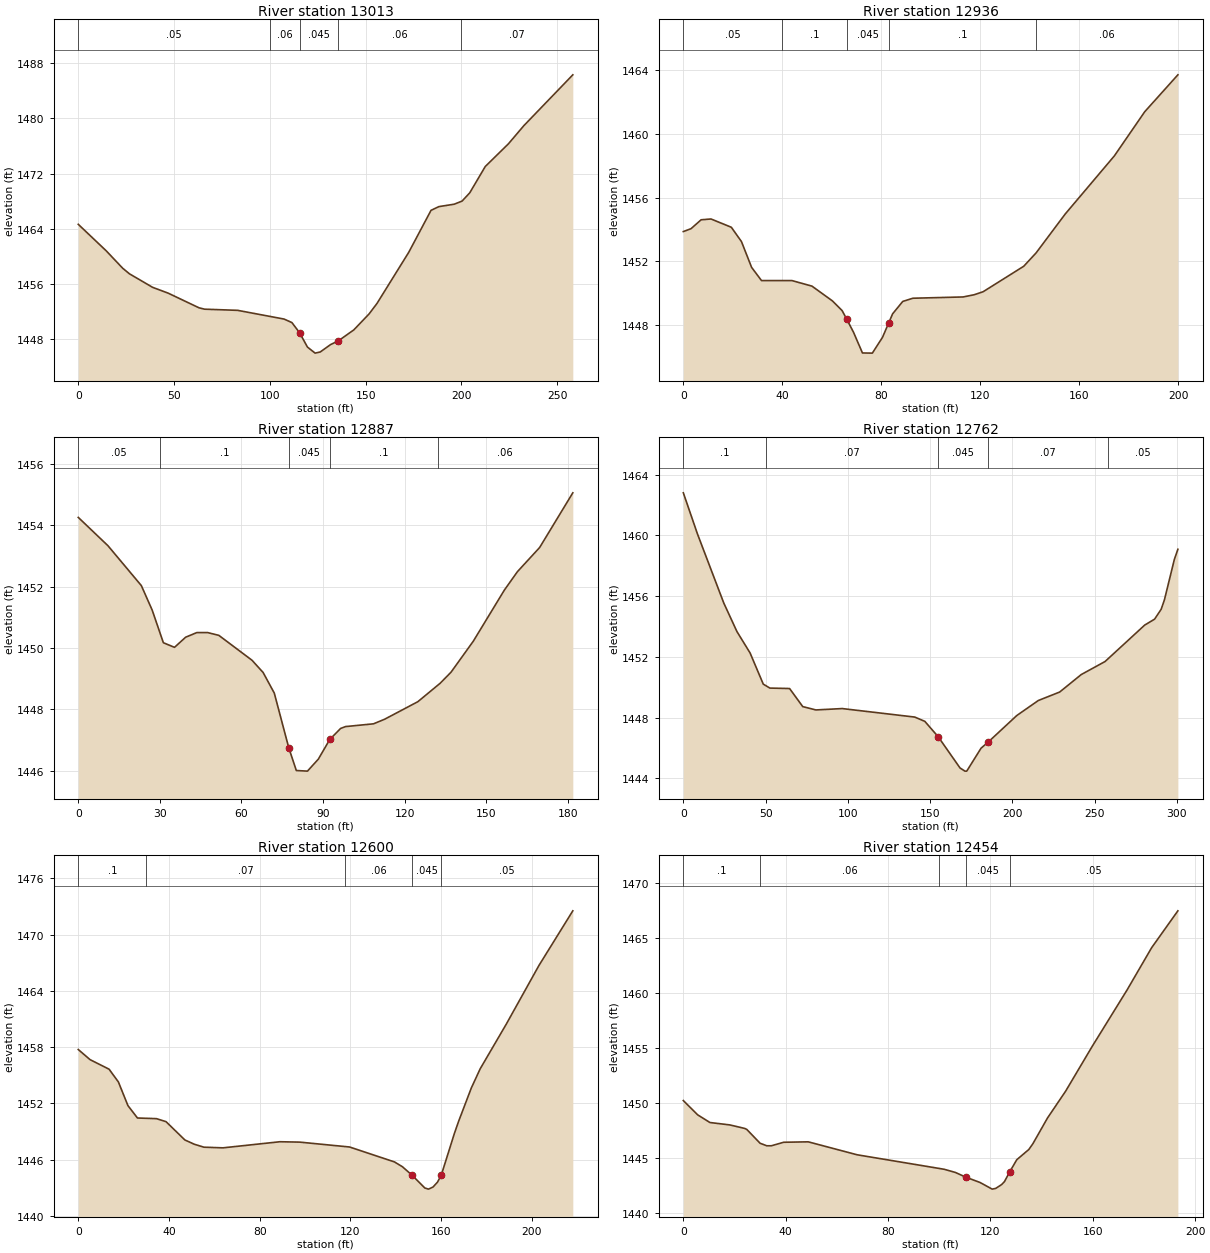
Type RM Length L Ch R = 1 ,13013   ,71.7,76.4,78.9
XS GIS Cut Line= 2
 2194237.7012709713812.8043456142194493.46450129713778.159127154
#Sta/Elev= 30
       0 1464.66    14.6 1460.82    23.2  1458.3    26.7  1457.5    38.8 1455.54
    46.9  1454.7      63 1452.58    65.9 1452.38    83.2 1452.21   107.4 1450.95
   111.5 1450.44   115.5 1448.97   119.6  1446.9   123.6 1446.02   126.3 1446.19
   131.7 1447.26   135.7 1447.79   143.8 1449.38   151.8  1451.7   155.9 1453.21
   172.5 1460.62   184.1 1466.68   188.2 1467.22   196.2 1467.57   200.3 1468.02
   204.3 1469.21   212.4 1473.02   224.5 1476.31   232.6 1478.95258.0991 1486.29
#Mann= 5 ,-1,0
       0     .05       0     100     .06       0   115.5    .045       0
   135.7     .06       0     200     .07       0
Bank Sta=115.5,135.7
XS Rating Curve= 0 ,0
Exp/Cntr(USF)=0,0
Exp/Cntr=0.3,0.1

Type RM Length L Ch R = 1 ,12936   ,52.6,49.1,54.4
XS GIS Cut Line= 4
2194293.13531845713855.5123025182194354.50828359713867.546217252
2194435.13551231713882.5886106712194489.28812862713894.020829668
#Sta/Elev= 30
       0 1453.87     3.1 1454.05     7.2 1454.61    11.2 1454.66    19.4 1454.14
    23.5 1453.24    27.6 1451.62    31.6 1450.79    43.9 1450.79      52 1450.44
    60.2 1449.52    64.2  1448.9    66.11448.347    68.8 1447.54    72.4 1446.24
    76.4 1446.23    80.5 1447.22      831448.122    84.6  1448.7    88.7 1449.48
    92.8 1449.68   113.1 1449.76   117.6  1449.9   121.2 1450.09   137.6 1451.69
   142.6 1452.53   154.4 1454.98   174.2 1458.62   186.5  1461.4   199.9 1463.72
#Mann= 5 ,-1,0
       0     .05       0      40      .1       0    66.1    .045       0
      83      .1       0  142.54     .06       0
Bank Sta=66.1,83
XS Rating Curve= 0 ,0
Exp/Cntr(USF)=0,0
Exp/Cntr=0.3,0.1

Type RM Length L Ch R = 1 ,12887   ,128,125.1,116.3
XS GIS Cut Line= 3
2194301.45861108 713900.74635296 2194352.6027487713910.975180484
2194480.16224489713934.441314216
#Sta/Elev= 30
       0 1454.25    10.9 1453.33    23.2 1452.03    27.2 1451.23    31.3 1450.17
    35.4 1450.02    39.5 1450.35    43.6  1450.5    47.6  1450.5    51.7 1450.41
    63.9  1449.6      68  1449.2    72.1 1448.53    77.41446.758    80.2 1446.01
    84.3 1445.99    88.3 1446.38    92.5 1447.02    96.5 1447.38    98.3 1447.44
   108.6 1447.53   112.7 1447.68   124.9 1448.25   133.1 1448.85   137.1 1449.21
   145.3 1450.22   156.7 1451.88   161.5 1452.48   169.7 1453.27   181.9 1455.05
#Mann= 5 ,-1,0
       0     .05       0      30      .1       0    77.4    .045       0
    92.5      .1       0  132.16     .06       0
Bank Sta=77.4,92.5
XS Rating Curve= 0 ,0
Exp/Cntr(USF)=0,0
Exp/Cntr=0.3,0.1

Type RM Length L Ch R = 1 ,12762   ,142.7,162.6,179.1
XS GIS Cut Line= 4
2194283.58694401714035.5330425142194409.34135299714037.939825461
 2194512.8330197 713994.016036682194569.39241895713967.541424265
#Sta/Elev= 30
       0  1462.8     8.6 1460.09    24.6 1455.54    32.6 1453.66    40.6 1452.25
    48.6  1450.2    52.6 1449.94    64.6 1449.91    72.6 1448.72    80.6  1448.5
    96.6 1448.59   140.7 1448.03   146.8 1447.75   154.9 1446.74   168.2 1444.68
   171.2 1444.47   172.3 1444.47     181 1445.98   185.3 1446.38   202.7 1448.13
   215.8 1449.12   228.8 1449.68   241.9 1450.83   256.4 1451.69   280.5 1454.09
   286.5 1454.48   290.5 1455.13   292.5 1455.76   298.5 1458.41300.6534 1459.08
#Mann= 5 ,-1,0
       0      .1       0      50     .07       0   154.9    .045       0
   185.3     .07       0   258.2     .05       0
Bank Sta=154.9,185.3
XS Rating Curve= 0 ,0
Exp/Cntr(USF)=0,0
Exp/Cntr=0.3,0.1

Type RM Length L Ch R = 1 ,12600   ,148.1,145.3,143.1
XS GIS Cut Line= 3
2194299.23103317 714096.906007662194392.49387236714125.787403022
 2194476.7312755714211.829893374
#Sta/Elev= 30
       0 1457.75     5.2 1456.67    13.6 1455.65    17.7 1454.29    21.9 1451.77
    26.1 1450.45    34.5 1450.38    38.7 1450.06      47 1448.11    51.2 1447.65
    55.4 1447.34    63.8 1447.27    88.9 1447.92    97.6 1447.88   119.6 1447.36
   139.4 1445.77   142.9 1445.26   147.2 1444.35   152.8 1442.99   154.4 1442.87
   156.4 1443.09   158.4 1443.62   160.1  1444.4   165.8 1448.78   167.7  1450.1
   173.3 1453.65   177.2 1455.69   188.7 1460.45   203.1  1466.7218.0453 1472.53
#Mann= 5 ,-1,0
       0      .1       0      30     .07       0  117.63     .06       0
   147.2    .045       0   160.1     .05       0
Bank Sta=147.2,160.1
XS Rating Curve= 0 ,0
Exp/Cntr(USF)=0,0
Exp/Cntr=0.3,0.1

Type RM Length L Ch R = 1 ,12454   ,228.2,223.7,215.2
XS GIS Cut Line= 2
2194247.48519981714216.6434592672194408.73965725714323.143604667
#Sta/Elev= 30
       0 1450.21     5.6 1448.91    10.4 1448.21    18.2 1447.99      24 1447.67
    24.8 1447.58      30 1446.32    32.6 1446.09    34.4 1446.09    39.2 1446.41
    48.8 1446.45    67.9 1445.27   101.9 1443.95   106.3 1443.66   110.6 1443.21
   115.9 1442.75   120.7 1442.14   122.1 1442.21   124.4 1442.56   125.5 1442.83
   127.6 1443.74   130.3 1444.82     135 1445.75   136.6 1446.28   142.3 1448.62
   149.4 1451.07   159.7 1455.12   173.4 1460.29     183 1464.14193.2493  1467.5
#Mann= 5 ,-1,0
       0      .1       0      30     .06       0     100     .05       0
   110.6    .045       0   127.6     .05       0
Bank Sta=110.6,127.6
XS Rating Curve= 0 ,0
Exp/Cntr(USF)=0,0
Exp/Cntr=0.3,0.1