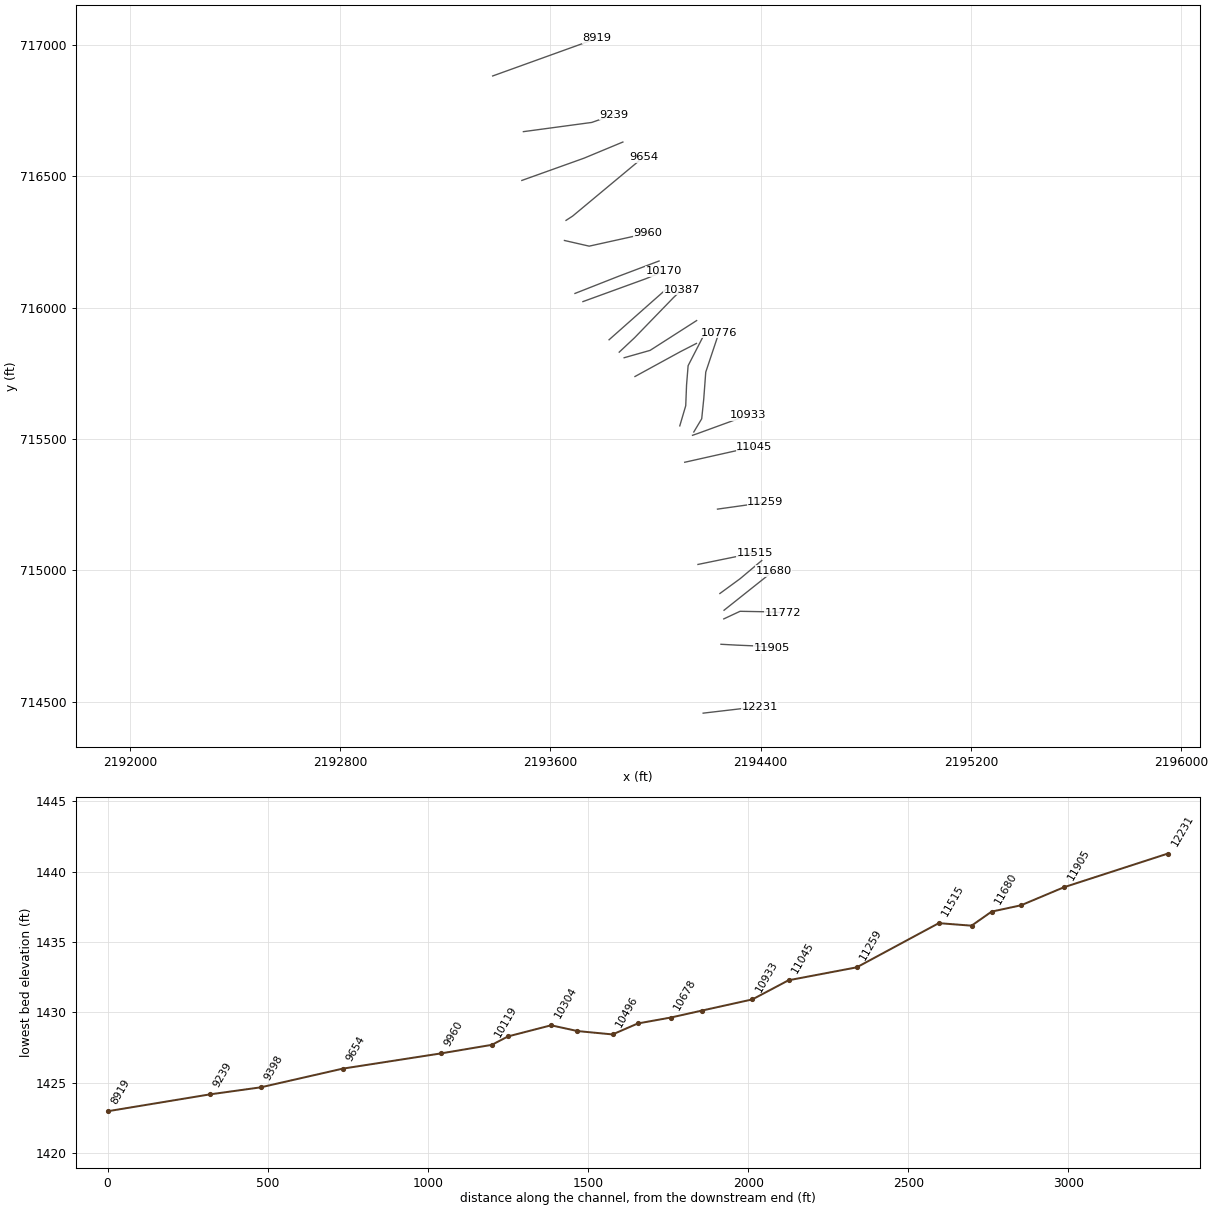
HEC-RAS study LISANDRN.prj: LISANDRN

--- LISANDRN.g01 (geometry) --- (continued)

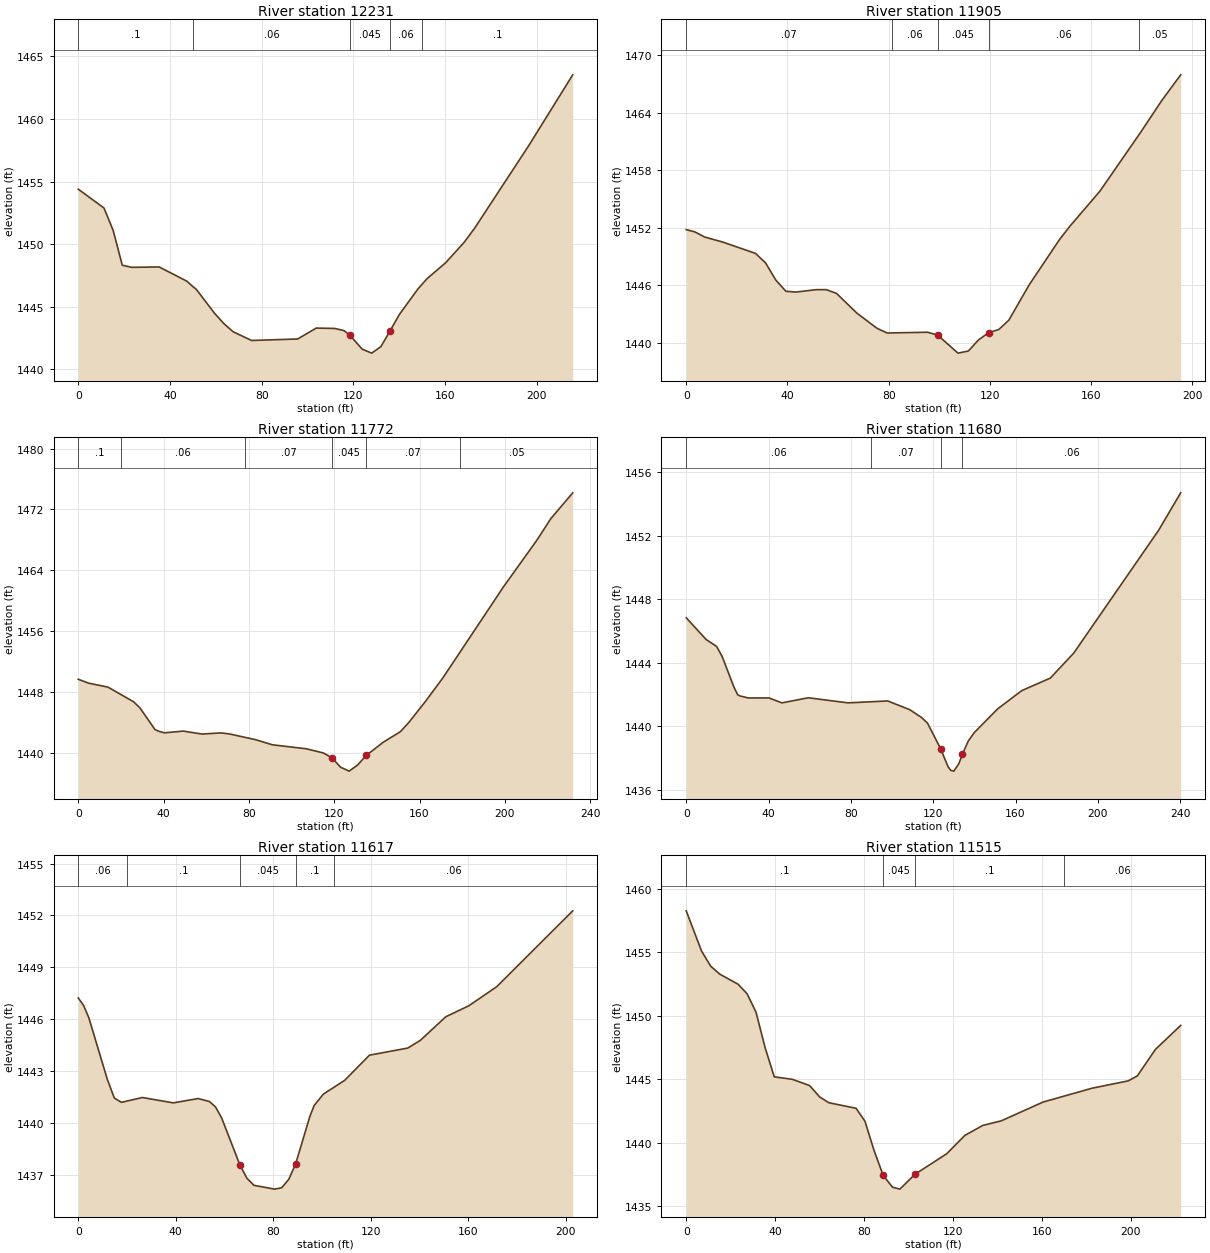
Type RM Length L Ch R = 1 ,12231   ,324.4,325.4,319.7
XS GIS Cut Line= 3
 2194181.0814269714456.7470973852194336.32494393714474.924325592
2194395.36934657714481.175944296
#Sta/Elev= 30
       0 1454.39    11.2 1452.89    15.2 1451.11    19.2 1448.32    23.3 1448.15
    35.3 1448.18    47.4 1447.04      50 1446.61    51.4 1446.41    59.5 1444.47
    63.5 1443.66    67.6    1443    75.6 1442.31    95.7 1442.43   103.8  1443.3
   111.9 1443.27   115.9  1443.1   118.5 1442.72   123.9 1441.61     128  1441.3
     132 1441.82     136 1443.07     140 1444.37   148.1 1446.41   152.1 1447.24
   160.2 1448.51   168.2 1450.12   172.8 1451.25   196.4 1457.84215.6785 1463.52
#Mann= 5 ,-1,0
       0      .1       0      50     .06       0   118.5    .045       0
     136     .06       0     150      .1       0
Bank Sta=118.5,136
XS Rating Curve= 0 ,0
Exp/Cntr(USF)=0,0
Exp/Cntr=0.3,0.1

Type RM Length L Ch R = 1 ,11905   ,133,133.6,133.2
XS GIS Cut Line= 4
2194248.85951331714718.7885538112194309.93699551714715.487068287
2194387.52190532714712.1855827632194443.64715922714704.757240335
#Sta/Elev= 30
       0 1451.78     3.3 1451.56     7.3 1451.01    14.5 1450.48    27.4  1449.3
    31.4  1448.3    35.4 1446.52    39.4 1445.35    43.4 1445.27    51.4 1445.52
    55.4 1445.52    59.4 1445.13    67.4 1443.08    75.4 1441.49    79.4    1441
    95.4 1441.08    99.4 1440.77   107.4  1438.9   111.5 1439.12   115.5 1440.28
   119.5 1441.03   123.5 1441.36   127.5 1442.34   135.5 1446.01   147.6 1450.78
   151.6 1452.13   163.5  1455.8   179.8 1462.02   187.9 1465.24   195.4 1467.93
#Mann= 5 ,-1,0
       0     .07       0   81.17     .06       0    99.4    .045       0
   119.5     .06       0  178.82     .05       0
Bank Sta=99.4,119.5
XS Rating Curve= 0 ,0
Exp/Cntr(USF)=0,0
Exp/Cntr=0.3,0.1

Type RM Length L Ch R = 1 ,11772   ,83.8,92,99
XS GIS Cut Line= 4
2194259.58934127714815.3570053842194321.49219484714844.245003717
2194412.28304675714842.5942609552194484.91572827714839.292775431
#Sta/Elev= 30
       0 1449.69     4.8 1449.18    13.9 1448.66    25.9 1446.74    28.9 1445.94
      36 1443.07    37.9 1442.84    40.4 1442.65    49.2 1442.88      58 1442.49
    66.9 1442.64      71  1442.5      83 1441.76      91 1441.08     107 1440.55
     115    1440     119 1439.35     123 1438.13     127 1437.62     131 1438.43
     135 1439.68     143 1441.42     151  1442.8     155 1444.02     163 1446.86
     171 1449.89   199.5 1461.89   215.1 1467.99   221.6 1470.81231.8252 1474.18
#Mann= 6 ,-1,0
       0      .1       0      20     .06       0   78.31     .07       0
     119    .045       0     135     .07       0  179.12     .05       0
Bank Sta=119,135
XS Rating Curve= 0 ,0
Exp/Cntr(USF)=0,0
Exp/Cntr=0.3,0.1

Type RM Length L Ch R = 1 ,11680   ,64.8,62.6,58.6
XS GIS Cut Line= 3
2194260.57886928 714848.243393032194343.77722213714914.401571099
2194448.59938751714997.764080576
#Sta/Elev= 30
       0 1446.83     9.7 1445.46    14.8 1445.02    17.5 1444.38    23.2 1442.46
      25 1441.98      26 1441.91    30.1 1441.78    40.2 1441.78    46.5 1441.47
    59.3 1441.79    78.6 1441.47    97.9 1441.59   108.6 1441.04   114.2 1440.56
   117.2  1440.2   123.6 1438.58   127.2 1437.45   128.5 1437.22     130 1437.17
   132.4 1437.63   134.2 1438.23     137 1439.06   139.9 1439.59   151.3 1441.09
     163 1442.24   176.9 1443.03   188.3 1444.61   229.5 1452.34240.2252  1454.7
#Mann= 4 ,-1,0
       0     .06       0      90     .07       0   123.6    .045       0
   134.2     .06       0
Bank Sta=123.6,134.2
XS Rating Curve= 0 ,0
Exp/Cntr(USF)=0,0
Exp/Cntr=0.3,0.1

Type RM Length L Ch R = 1 ,11617   ,107.2,102.4,96.5
XS GIS Cut Line= 3
2194244.73265641714911.9254569562194321.49219484714968.050710862
2194404.02933294715037.381906862
#Sta/Elev= 30
       0 1447.23     2.1 1446.82     4.3  1446.1    11.9 1442.53    14.8 1441.44
    17.7 1441.19    26.3 1441.47      39 1441.16    49.2 1441.41    53.8 1441.24
    56.3 1440.93    58.8  1440.3    66.3 1437.58    69.2  1436.8    72.1 1436.39
    80.6 1436.17    83.5 1436.25    86.4 1436.74    89.2 1437.63      95 1440.36
    96.8 1441.01   100.6 1441.67   109.3 1442.46   119.5 1443.92   135.2 1444.33
   140.4 1444.78   150.8 1446.14   160.3 1446.78   171.7 1447.88   202.9 1452.27
#Mann= 5 ,-1,0
       0     .06       0      20      .1       0    66.3    .045       0
    89.2      .1       0  105.09     .06       0
Bank Sta=66.3,89.2
XS Rating Curve= 0 ,0
Exp/Cntr(USF)=0,0
Exp/Cntr=0.3,0.1

Type RM Length L Ch R = 1 ,11515   ,255.8,256,254.1
XS GIS Cut Line= 2
2194161.37014693715022.5252220052194379.26819151715067.095276577
#Sta/Elev= 30
       0 1458.28     6.9 1455.11      11 1453.92    15.1 1453.29    23.3  1452.5
    27.4 1451.74    31.4 1450.29    35.5 1447.49    39.6  1445.2    47.8    1445
    55.5 1444.51      60 1443.62    64.1 1443.16    76.4 1442.72    80.4  1441.7
    84.5 1439.39    88.6 1437.43    92.8  1436.5    96.1 1436.35   102.9 1437.52
   117.2 1439.14   125.3 1440.58   133.4 1441.37   141.7 1441.73   160.5 1443.21
   182.5  1444.3   198.8 1444.88   202.9 1445.27   211.1 1447.37222.4096 1449.25
#Mann= 4 ,-1,0
       0      .1       0    88.6    .045       0   102.9      .1       0
     170     .06       0
Bank Sta=88.6,102.9
XS Rating Curve= 0 ,0
Exp/Cntr(USF)=0,0
Exp/Cntr=0.3,0.1

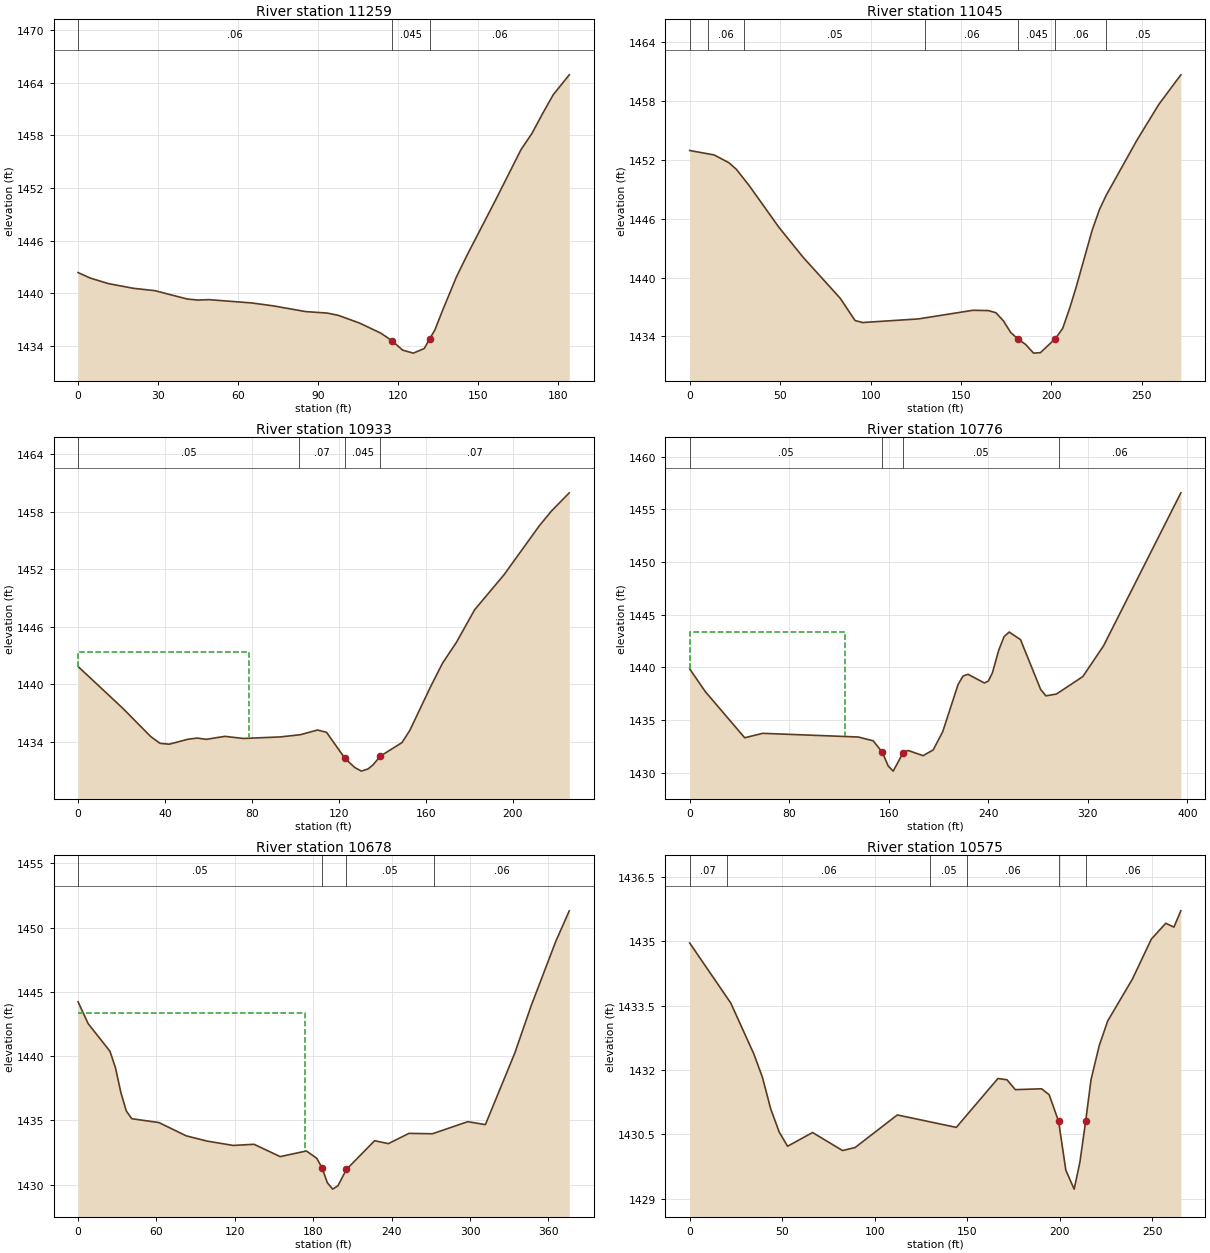
Type RM Length L Ch R = 1 ,11259   ,212.4,213.1,213.7
XS GIS Cut Line= 2
2194235.65357122715232.9949241512194418.06064641 715258.58143696
#Sta/Elev= 30
       0 1442.38     4.6 1441.75    11.3 1441.13    20.7 1440.59    28.8 1440.32
    40.9 1439.37      45 1439.25      49  1439.3    65.2 1438.92    73.2 1438.59
    85.3 1437.94    93.4 1437.77    97.5 1437.52   105.5 1436.64   113.6 1435.47
   117.7 1434.62   121.7 1433.55   125.7 1433.21   129.8 1433.73   131.9 1434.86
   133.8 1435.85   136.6 1438.01   141.9  1441.9   145.9 1444.38   156.5  1450.6
   166.1 1456.38   170.2 1458.22   174.2 1460.48   178.2 1462.63184.1929 1464.89
#Mann= 3 ,-1,0
       0     .06       0   117.7    .045       0   131.9     .06       0
Bank Sta=117.7,131.9
XS Rating Curve= 0 ,0
Exp/Cntr(USF)=0,0
Exp/Cntr=0.3,0.1

Type RM Length L Ch R = 1 ,11045   ,111.3,112.9,114.1
XS GIS Cut Line= 2
2194111.02249269715411.2751424382194375.96670598715470.701881868
#Sta/Elev= 30
       0 1452.96    13.5 1452.51    21.7 1451.71    25.8 1451.04    32.7 1449.43
    49.4 1445.11    62.7 1442.07    83.2 1437.89    91.4 1435.62    95.5 1435.41
   126.4 1435.78   156.6 1436.66   165.2 1436.63   169.3 1436.41   173.4 1435.59
   177.5 1434.39   181.6 1433.71   185.7 1433.18   190.1 1432.29   193.9 1432.34
   202.1 1433.76   206.2 1434.81   210.2 1436.95   213.5 1438.93   222.5 1444.83
   226.6 1446.97   230.2 1448.37   247.1 1453.97   259.4 1457.68271.5271 1460.68
#Mann= 7 ,-1,0
       0     .05       0      10     .06       0      30     .05       0
     130     .06       0   181.6    .045       0   202.1     .06       0
     230     .05       0
Bank Sta=181.6,202.1
XS Rating Curve= 0 ,0
Exp/Cntr(USF)=0,0
Exp/Cntr=0.3,0.1

Type RM Length L Ch R = 1 ,10933   ,139.9,156.8,178.9
XS GIS Cut Line= 4
2194140.66226962715513.850910793  2194160.929988715520.839779198
2194308.39511135715574.6540659222194353.12386915715590.728463254
#Sta/Elev= 30
       0 1441.85    20.6 1437.48    33.4 1434.54    37.7 1433.83    41.9 1433.74
    50.4 1434.25    54.7 1434.38      59 1434.25    67.5 1434.56      76 1434.34
      93  1434.5   102.2 1434.73   110.1 1435.22   114.3 1434.98   122.8 1432.25
   127.2 1431.32   130.3 1430.93   133.4 1431.16   135.6 1431.57   139.1  1432.5
     149 1433.91   152.6 1435.18   162.4 1439.86   167.7 1442.22     174 1444.36
   182.4 1447.77   195.9 1451.42   212.2 1456.55   217.7 1458.07225.9458 1459.98
#Mann= 4 ,-1,0
       0     .05       0  101.44     .07       0   122.8    .045       0
   139.1     .07       0
#XS Ineff= 2 , 0
         78.5515 1443.38
Permanent Ineff=
       T       F
Bank Sta=122.8,139.1
XS Rating Curve= 0 ,0
Exp/Cntr(USF)=0,0
Exp/Cntr=0.3,0.1

Type RM Length L Ch R = 1 ,10776   ,94.9,98.1,89.5
XS GIS Cut Line= 5
 2194145.4717992715526.4175950732194175.60661165715576.750726443
 2194183.2943669715651.5316183832194190.98212214715754.267983945
2194241.04876796715904.046422745
#Sta/Elev= 30
       0 1439.85    12.7 1437.67    44.2 1433.31    58.7 1433.73   135.5 1433.38
   147.5 1433.02   154.9 1431.92   159.6 1430.62   163.6 1430.14   171.6  1431.9
   175.6  1432.1   187.6 1431.61   195.7 1432.15   203.4 1433.89   215.7 1438.36
   219.7 1439.17   223.7 1439.34   236.9 1438.51   240.1  1438.7   243.3 1439.47
   248.4 1441.62   252.7 1442.91   256.8 1443.35   265.9 1442.63   282.1  1437.9
   286.3 1437.29   294.8 1437.46     316 1439.12   332.7 1442.05   394.8 1456.57
#Mann= 4 ,-1,0
       0     .05       0   154.9    .045       0   171.6     .05       0
  296.86     .06       0
#XS Ineff= 2 , 0
        124.8267 1443.38
Permanent Ineff=
       T       F
Bank Sta=154.9,171.6
XS Rating Curve= 0 ,0
Exp/Cntr(USF)=0,0
Exp/Cntr=0.3,0.1

Type RM Length L Ch R = 1 ,10678   ,115.3,102.8,87.8
XS GIS Cut Line= 5
2194092.18705903715549.7744631732194114.80345652715626.371692123
2194117.91077731715704.7863763022194123.88898545715778.729023365
 2194189.5489778715906.296817406
#Sta/Elev= 30
       0 1444.22     7.7 1442.52    24.4 1440.37    28.6 1439.09    32.7 1437.18
    36.9 1435.72    41.1 1435.12    61.9 1434.82    82.7 1433.79    98.7 1433.38
   118.7 1433.04   134.7 1433.13   154.7 1432.17   174.8 1432.61   182.8 1432.03
   186.8 1431.28   190.8 1430.14   194.9 1429.64   198.9  1429.9   205.4 1431.17
     227 1433.41   237.5 1433.18   253.3 1433.98   271.3 1433.95   298.3 1434.89
   311.8 1434.66   334.3 1440.23   346.8  1443.9   365.7 1448.93376.0005  1451.3
#Mann= 4 ,-1,0
       0     .05       0   186.8    .045       0   205.4     .05       0
  272.53     .06       0
#XS Ineff= 2 , 0
        173.3495 1443.38
Permanent Ineff=
       T       F
Bank Sta=186.8,205.4
XS Rating Curve= 0 ,0
Exp/Cntr(USF)=0,0
Exp/Cntr=0.3,0.1

Type RM Length L Ch R = 1 ,10575   ,75.9,78.8,79.6
XS GIS Cut Line= 3
2193921.73908257 715737.524419242194094.90771084715832.262413182
2194155.47790369 715863.32405054
#Sta/Elev= 30
       0 1434.96    22.2 1433.56    34.7 1432.37    39.3 1431.83    43.8 1431.09
    48.4 1430.55    52.9 1430.22    66.4 1430.54    82.6 1430.12    89.4 1430.19
   112.2 1430.95   144.1 1430.66   166.6  1431.8   171.5 1431.77     176 1431.54
   190.2 1431.56   194.3 1431.42   199.4  1430.8   203.3 1429.66   207.8 1429.22
   210.9 1429.85     214  1430.8   216.9 1431.77   221.3 1432.56   225.9 1433.14
   239.3 1434.12   249.5 1435.05   257.3 1435.42   261.7 1435.33  265.46 1435.71
#Mann= 6 ,-1,0
       0     .07       0      20     .06       0     130     .05       0
     150     .06       0   199.4    .045       0     214     .06       0
Bank Sta=199.4,214
XS Rating Curve= 0 ,0
Exp/Cntr(USF)=0,0
Exp/Cntr=0.3,0.1

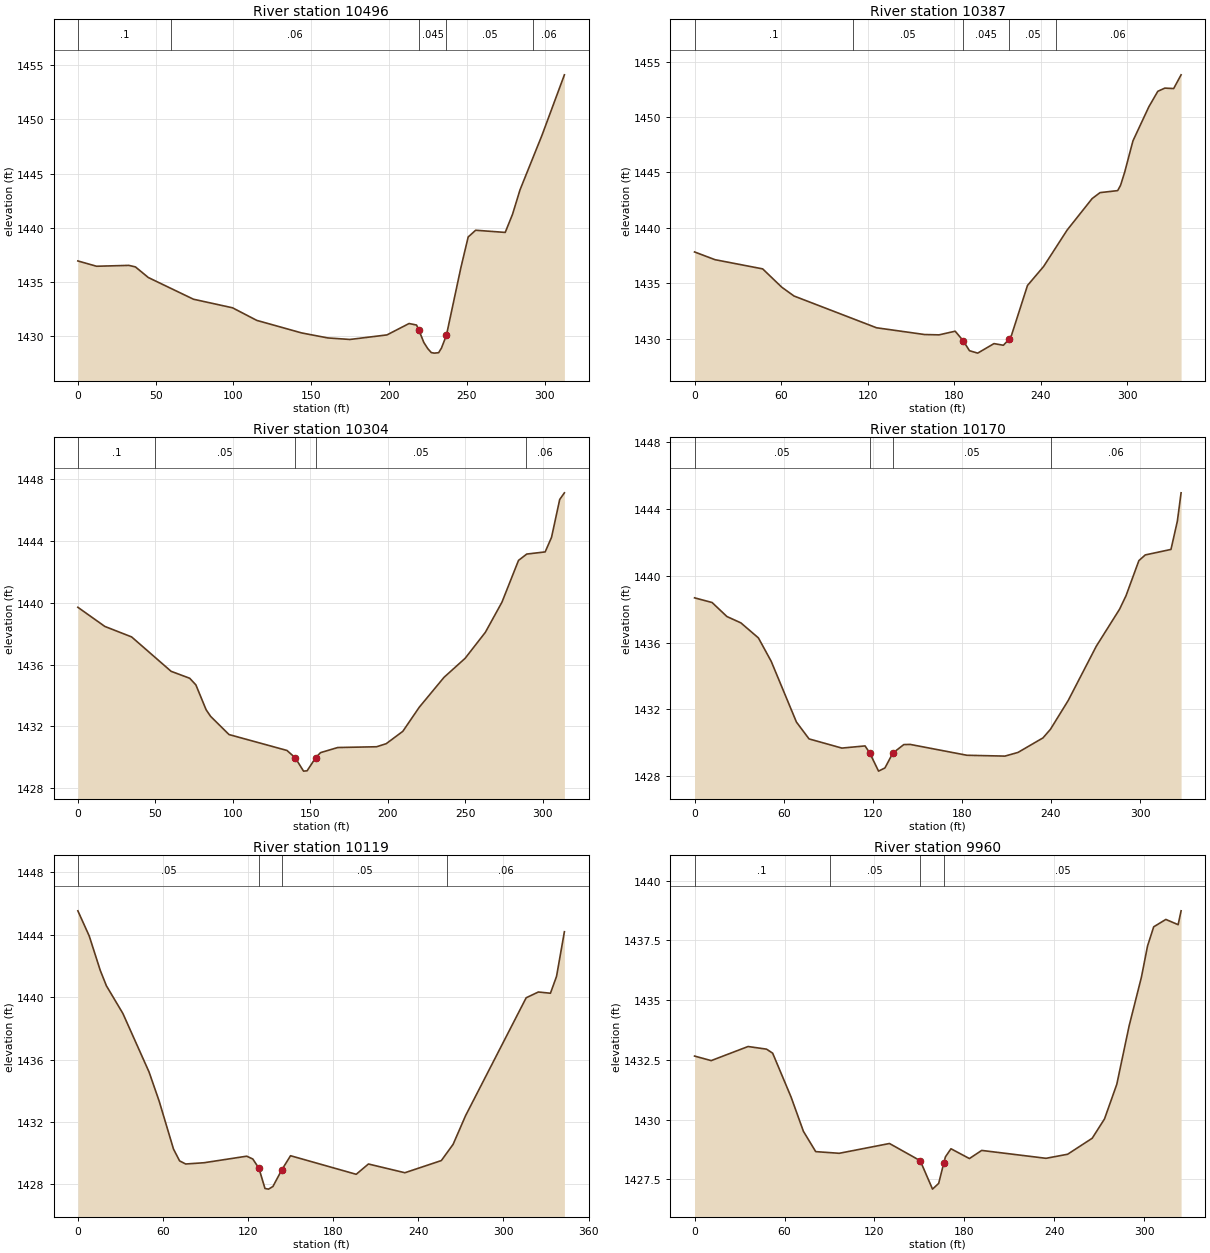
Type RM Length L Ch R = 1 ,10496   ,108.2,109.6,109.8
XS GIS Cut Line= 3
2193880.58241307715808.9661851642193979.20311168715836.921658786
2194156.25444462715950.296635143
#Sta/Elev= 30
       0 1436.94      12 1436.45    32.8 1436.53      37 1436.39    45.3 1435.41
    74.3 1433.41    99.4 1432.62     115 1431.46   143.9  1430.3   160.7 1429.84
   174.9  1429.7   198.7 1430.12   212.9 1431.17   217.7 1431.03   219.2 1430.56
   222.4 1429.42     225 1428.84   227.2 1428.49   229.1 1428.44   231.9 1428.48
   233.7  1428.9   236.9 1430.08   246.2 1436.32   250.9 1439.15   255.7 1439.77
   274.7 1439.57   279.4 1441.24   284.2 1443.49   298.4 1448.55312.7468  1454.1
#Mann= 5 ,-1,0
       0      .1       0      60     .06       0   219.2    .045       0
   236.9     .05       0  292.51     .06       0
Bank Sta=219.2,236.9
XS Rating Curve= 0 ,0
Exp/Cntr(USF)=0,0
Exp/Cntr=0.3,0.1

Type RM Length L Ch R = 1 ,10387   ,76.6,82.3,86.3
XS GIS Cut Line= 4
2193861.80341519715830.188225795 2193920.1860007715885.067196691
2194068.50531908 716038.045760682194100.34349737716068.330857105
#Sta/Elev= 30
       0 1437.82    14.2 1437.12    47.2 1436.29    60.4 1434.64    68.9 1433.84
   126.1 1430.97   159.4 1430.36   169.4 1430.33   180.6 1430.66   186.1 1429.81
   190.5  1428.9   196.2 1428.68   207.5 1429.54     214 1429.39     218 1429.94
   219.6 1430.28   230.7 1434.79   241.9 1436.51   258.2  1439.8   275.5 1442.64
     281 1443.18   293.2 1443.36   295.2 1443.84     298    1445   303.8 1447.86
   314.8 1450.93     321 1452.33   325.9 1452.62     332 1452.58337.1431 1453.82
#Mann= 5 ,-1,0
       0      .1       0  110.13     .05       0   186.1    .045       0
     218     .05       0  250.13     .06       0
Bank Sta=186.1,218
XS Rating Curve= 0 ,0
Exp/Cntr(USF)=0,0
Exp/Cntr=0.3,0.1

Type RM Length L Ch R = 1 ,10304   ,139,134.4,130.1
XS GIS Cut Line= 3
2193823.11838395715877.3017873522193972.21424327716009.313746124
2194058.41028694716085.414757652
#Sta/Elev= 30
       0 1439.71    17.4 1438.47    34.7 1437.79    60.2 1435.56    72.2 1435.11
    76.2 1434.68    82.8 1433.07    85.7 1432.64    97.6 1431.46     135 1430.43
   140.3 1429.96   145.7 1429.09     148 1429.11   153.6 1429.97   156.7 1430.29
   167.8 1430.62   192.9 1430.67   199.1 1430.87   209.8 1431.67   220.4 1433.23
   236.4 1435.17     250  1436.4   263.1 1438.09   273.8 1440.04   284.5 1442.75
   289.8 1443.16   301.7  1443.3   305.8 1444.24   311.1  1446.7314.1231 1447.13
#Mann= 5 ,-1,0
       0      .1       0      50     .05       0   140.3    .045       0
   153.6     .05       0  289.14     .06       0
Bank Sta=140.3,153.6
XS Rating Curve= 0 ,0
Exp/Cntr(USF)=0,0
Exp/Cntr=0.3,0.1

Type RM Length L Ch R = 1 ,10170   ,49.7,50.8,48.7
XS GIS Cut Line= 3
2193723.72114441716022.5149420012193962.89575206716109.487526604
2194030.45481332716137.443000227
#Sta/Elev= 30
       0 1438.68    11.8  1438.4    21.8 1437.56    31.2 1437.18      43 1436.28
    51.6 1434.88    68.6 1431.24    77.1 1430.23    99.2 1429.68   114.8 1429.81
   117.9  1429.4   123.9  1428.3   128.2 1428.49   133.5 1429.38   140.9 1429.89
   145.2  1429.9   183.4 1429.25     209  1429.2   217.8 1429.42   234.6 1430.29
   239.6  1430.8   251.6 1432.53   270.5 1435.78   286.2    1438   290.5  1438.8
   299.2 1440.91   303.5 1441.25   320.8 1441.58   325.1 1443.27327.6115 1444.97
#Mann= 4 ,-1,0
       0     .05       0   117.9    .045       0   133.5     .05       0
     240     .06       0
Bank Sta=117.9,133.5
XS Rating Curve= 0 ,0
Exp/Cntr(USF)=0,0
Exp/Cntr=0.3,0.1

Type RM Length L Ch R = 1 ,10119   ,158.5,159.2,153.7
XS GIS Cut Line= 3
2193693.43604798716053.5765793592193861.16888972716119.582558746
2194013.37091277716177.046587858
#Sta/Elev= 30
       0 1445.53       8 1443.92    15.8 1441.71    20.1 1440.73    31.7 1438.96
    50.2  1435.2    57.3 1433.34    67.4 1430.27    71.7 1429.51      76 1429.31
    88.9 1429.39     119 1429.81   123.3 1429.63   127.6 1429.04   131.9 1427.74
   134.4  1427.7   137.5 1427.87   143.7 1428.93   149.9 1429.84   196.2 1428.65
   204.8 1429.31   230.5 1428.75   256.2 1429.53   264.5 1430.57   273.3 1432.41
     316 1439.96   324.6 1440.33   333.1 1440.25   337.4 1441.33342.9414 1444.19
#Mann= 4 ,-1,0
       0     .05       0   127.6    .045       0   143.7     .05       0
  260.25     .06       0
Bank Sta=127.6,143.7
XS Rating Curve= 0 ,0
Exp/Cntr(USF)=0,0
Exp/Cntr=0.3,0.1

Type RM Length L Ch R = 1 ,9960    ,294,306,305.7
XS GIS Cut Line= 3
2193653.40104872716255.0458105582193747.44878405716233.475229059
2193970.05718512716282.656154876
#Sta/Elev= 30
       0 1432.66    11.1 1432.47    35.7 1433.06      48 1432.95    52.1 1432.78
    64.4 1430.94    72.6 1429.51    80.8 1428.66    96.5 1428.59     130    1429
   150.5 1428.28   158.7 1427.09   162.8 1427.33   166.2 1428.18   167.3 1428.44
     171 1428.78   183.3 1428.37   191.5 1428.71   234.4 1428.38   248.8 1428.55
   265.2 1429.22   273.4 1430.03   281.6 1431.48   289.8 1433.92     298 1435.96
   302.1 1437.27   306.2 1438.07   314.3 1438.38   322.5 1438.16324.4662 1438.74
#Mann= 4 ,-1,0
       0      .1       0      90     .05       0   150.5    .045       0
   166.2     .05       0
Bank Sta=150.5,166.2
XS Rating Curve= 0 ,0
Exp/Cntr(USF)=0,0
Exp/Cntr=0.3,0.1

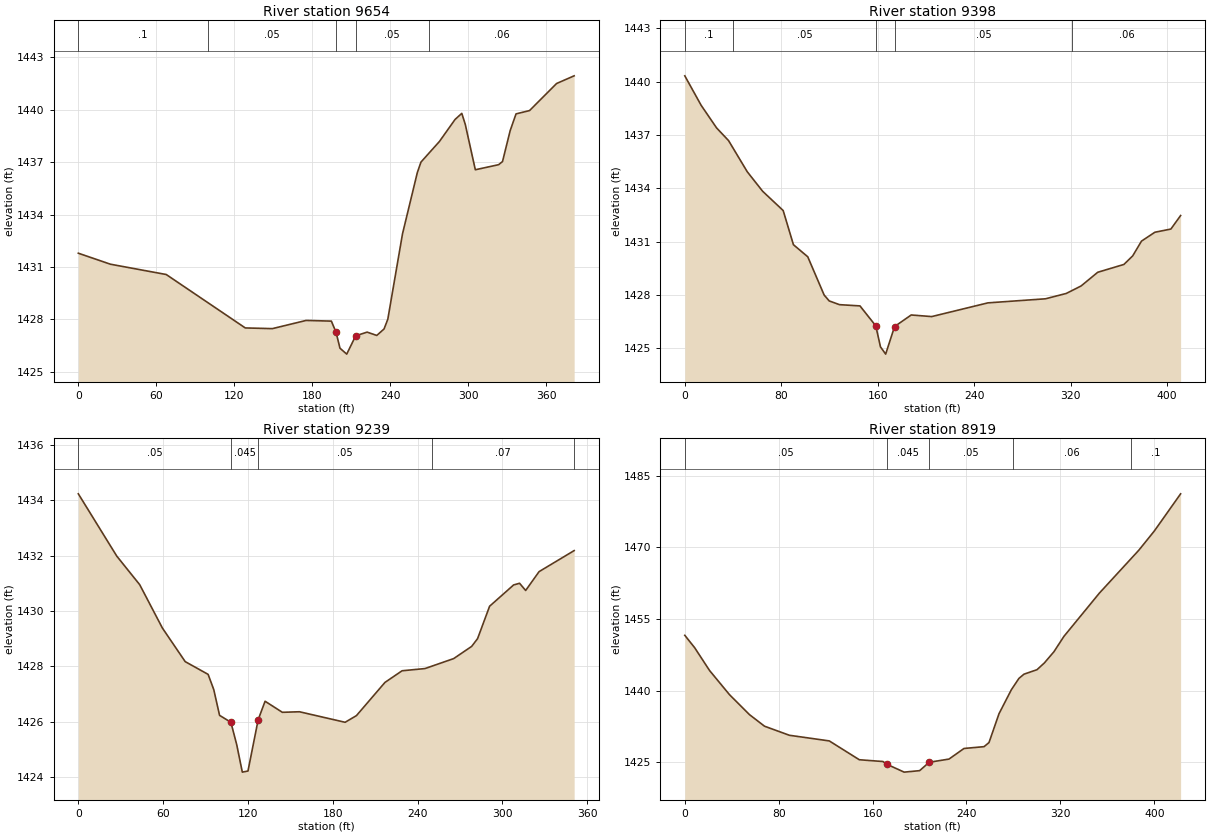
Type RM Length L Ch R = 1 ,9654    ,254.3,256.3,243.1
XS GIS Cut Line= 3
2193659.40479299716331.5572172932193684.24517203716347.630403731
2193954.56694393716572.655013855
#Sta/Elev= 30
       0 1431.79    24.7 1431.16    67.6 1430.57   128.4 1427.51   149.2 1427.47
   175.2 1427.94   194.6  1427.9   198.2 1427.26   201.2 1426.35   206.4 1426.01
   213.3 1427.06   222.1 1427.27   229.5 1427.08   235.1 1427.45     238 1428.01
   249.3  1432.9   260.7 1436.41   263.5 1437.01   277.7 1438.19   289.7 1439.45
   294.9  1439.8   297.6 1439.16   305.3 1436.57   323.2 1436.86   326.2 1437.04
   332.1 1438.81   336.6 1439.77     347 1439.96   367.8 1441.51   381.3 1441.95
#Mann= 5 ,-1,0
       0      .1       0   99.59     .05       0   198.2    .045       0
   213.3     .05       0  269.59     .06       0
Bank Sta=198.2,213.3
XS Rating Curve= 0 ,0
Exp/Cntr(USF)=0,0
Exp/Cntr=0.3,0.1

Type RM Length L Ch R = 1 ,9398    ,158.7,158.6,153.3
XS GIS Cut Line= 3
2193491.36693478716483.5218890662193728.08113504716568.271417554
2193875.66221051 716629.64176577
#Sta/Elev= 30
       0 1440.32    13.6 1438.66    26.4 1437.39    36.3 1436.68    51.8 1434.93
    64.6 1433.83    81.6 1432.75    90.1 1430.83     102 1430.15   115.6    1428
   119.8 1427.67   128.3 1427.46   145.3 1427.39   158.4 1426.27   162.3 1425.09
   166.6 1424.68     174 1426.23   187.8 1426.88   204.8 1426.79   251.4 1427.56
   299.2 1427.79   316.4 1428.09   328.7 1428.51   342.5 1429.28   364.2 1429.72
   371.5  1430.2   378.8 1431.03   389.9 1431.53   403.2 1431.71411.2608 1432.47
#Mann= 5 ,-1,0
       0      .1       0      40     .05       0   158.4    .045       0
     174     .05       0  321.43     .06       0
Bank Sta=158.4,174
XS Rating Curve= 0 ,0
Exp/Cntr(USF)=0,0
Exp/Cntr=0.3,0.1

Type RM Length L Ch R = 1 ,9239    ,301.4,319.5,305.2
XS GIS Cut Line= 3
2193497.21172985 716669.094132482193757.30511038716704.162902889
 2193840.5934401 716733.38687823
#Sta/Elev= 30
       0 1434.23    27.2 1431.98    43.4 1430.95    59.5 1429.38    75.6 1428.17
    91.8 1427.71    95.8 1427.16    99.9 1426.23   107.9 1425.98     112 1425.18
     116 1424.18     120 1424.22   127.2 1426.07   132.1 1426.74   144.3 1426.34
   156.4 1426.36   188.7 1425.98   196.7 1426.22   216.9 1427.42     229 1427.84
   245.2 1427.92   265.5 1428.28   278.2 1428.72   282.4    1429   290.9 1430.17
   307.9 1430.94   312.1    1431   316.4 1430.74   325.9 1431.42350.7135 1432.18
#Mann= 5 ,-1,0
       0     .05       0   107.9    .045       0   127.2     .05       0
     250     .07       0  350.71     .05       0
Bank Sta=107.9,127.2
XS Rating Curve= 0 ,0
Exp/Cntr(USF)=0,0
Exp/Cntr=0.3,0.1

Type RM Length L Ch R = 1 ,8919    ,189.6,194.6,193.1
XS GIS Cut Line= 2
2193380.31582848716880.9679537012193777.76189312717024.165432871
#Sta/Elev= 30
       0  1451.6     8.4 1449.01    21.1 1444.24    38.1 1439.18    55.1 1435.01
    67.9 1432.59    89.1 1430.69   123.1 1429.51   148.7 1425.57   168.8  1425.2
   172.2 1424.62   186.9 1422.98   200.1 1423.29   208.2 1425.04   225.1 1425.71
   237.9 1427.93     255 1428.31   259.2 1429.17   267.7 1435.19   278.2  1440.2
   284.7 1442.59     289 1443.47   300.1 1444.41   306.4 1445.83   314.5 1448.16
     323 1451.37   353.2 1460.42   386.8 1469.39   400.1 1473.44422.4558  1481.2
#Mann= 5 ,-1,0
       0     .05       0   172.2    .045       0   208.2     .05       0
     280     .06       0     380      .1       0
Bank Sta=172.2,208.2
XS Rating Curve= 0 ,0
Exp/Cntr(USF)=0,0
Exp/Cntr=0.3,0.1