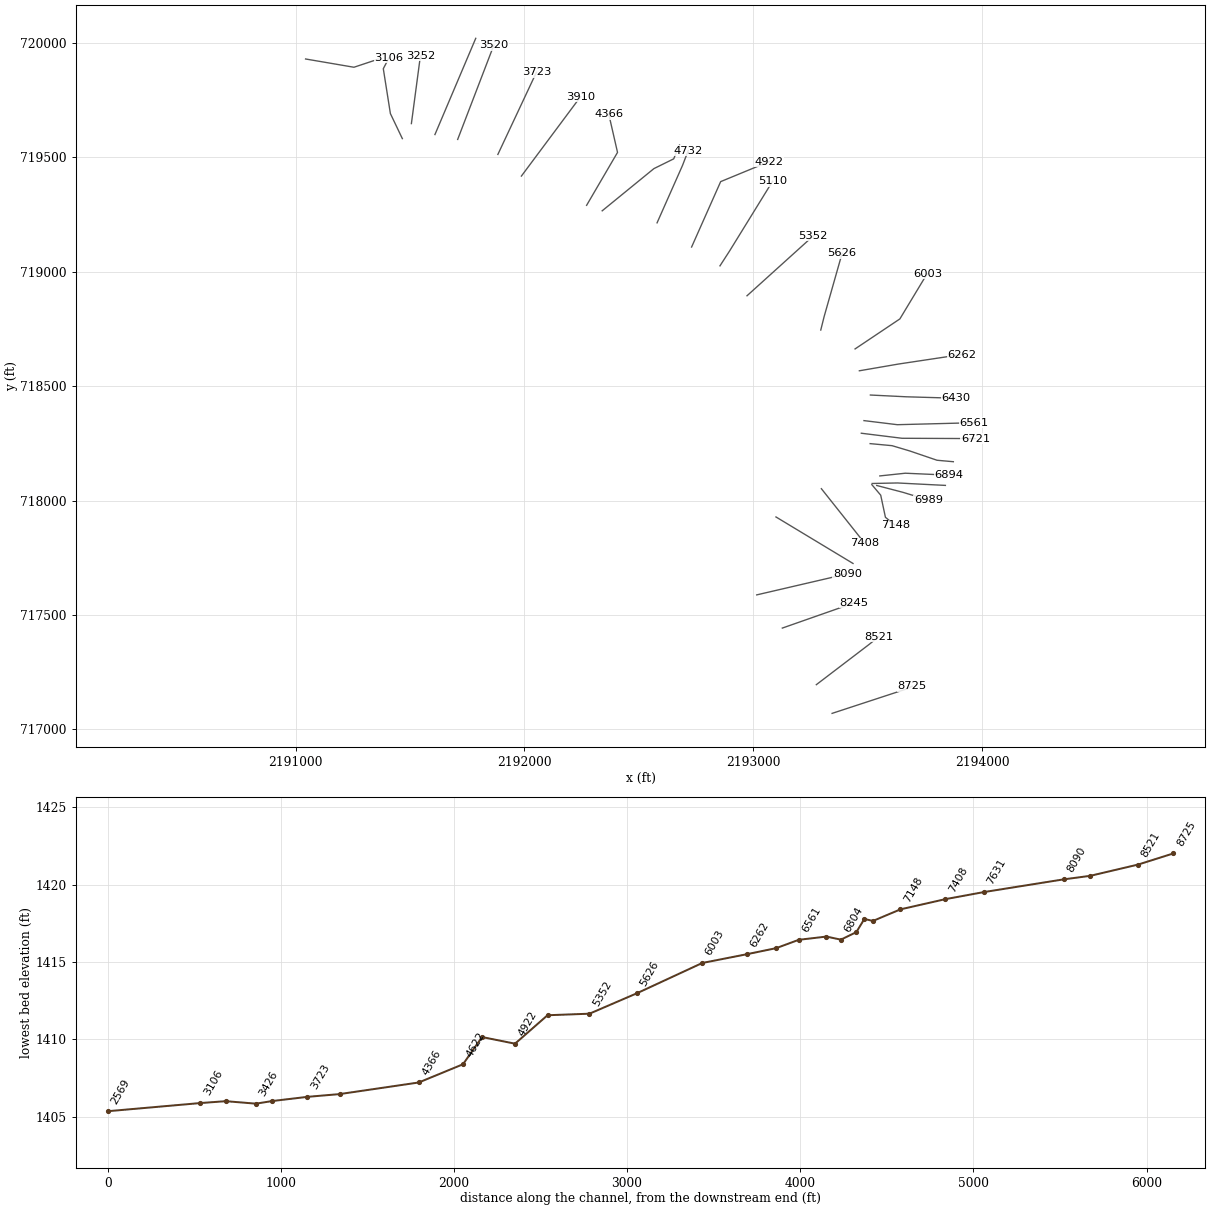
HEC-RAS study LISANDRN.prj: LISANDRN

--- LISANDRN.g01 (geometry) --- (continued)

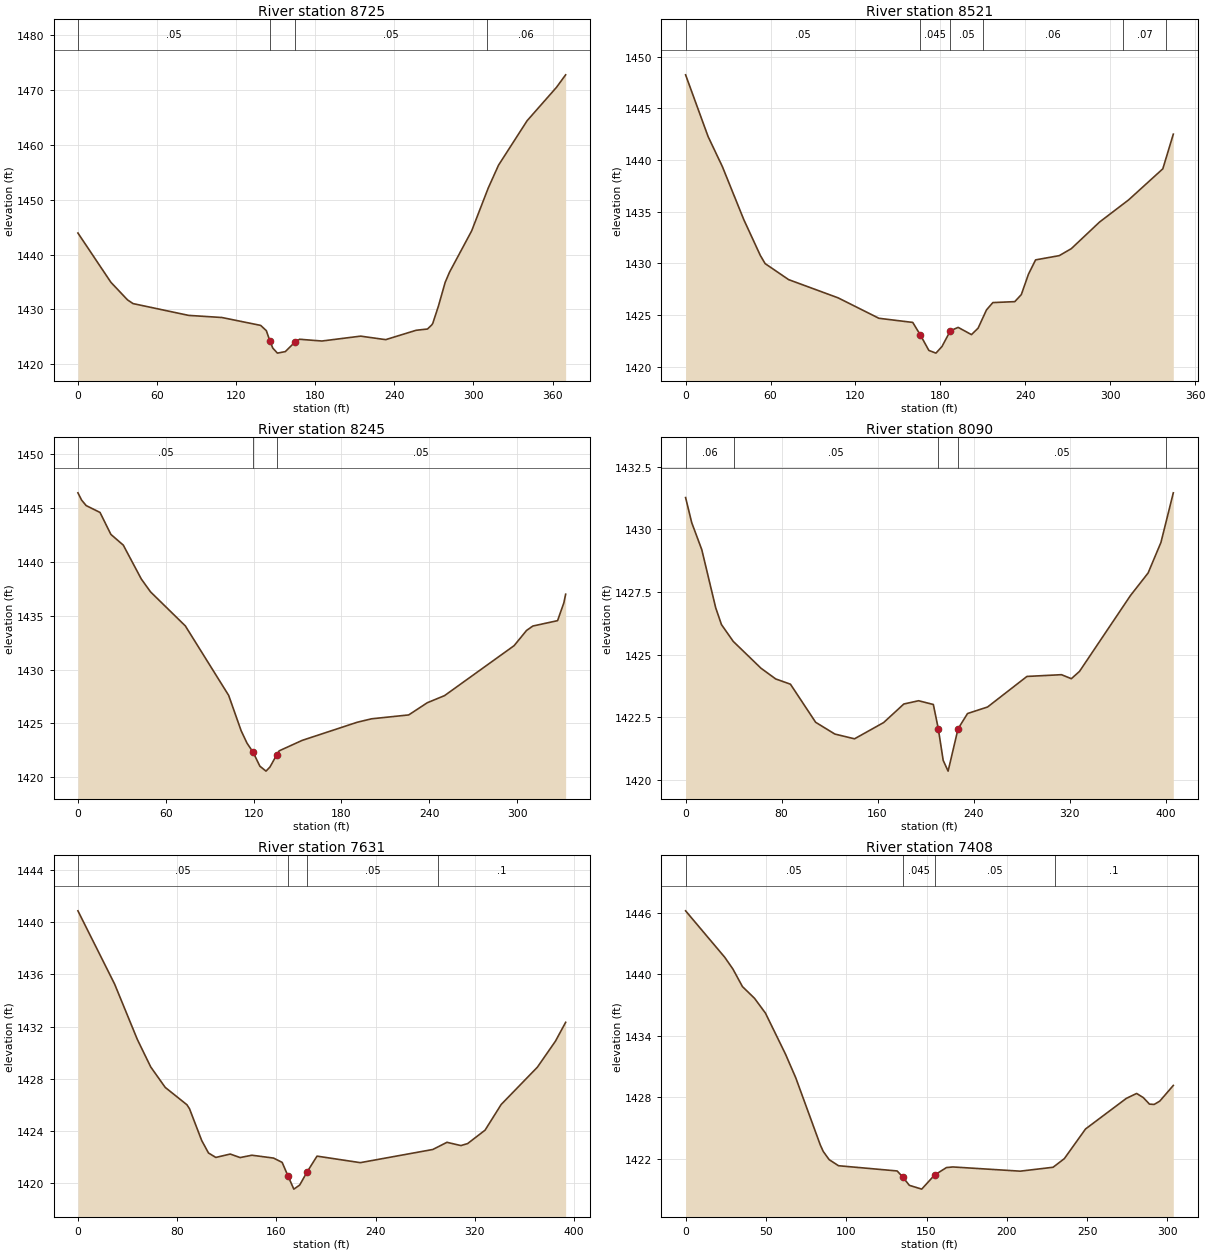
Type RM Length L Ch R = 1 ,8725    ,197.2,203.4,207.2
XS GIS Cut Line= 3
2193344.42878677717070.4269858362193669.31902662717176.948375953
 2193694.4735634717189.280893547
#Sta/Elev= 30
       0 1443.95      25 1434.96    37.6 1431.75    41.8 1431.07    83.9 1428.92
   109.2 1428.53   138.6 1427.09   142.9 1426.13   145.6 1424.26   147.8 1422.95
   151.3 1422.03   157.3 1422.31   164.4    1424   168.1 1424.56     185 1424.24
   214.4 1425.13   233.4 1424.49   256.5  1426.2   265.1 1426.43   268.3 1427.16
   269.1 1427.44   273.4  1430.6   278.5 1434.92   281.8 1436.79   298.6 1444.33
   311.2 1452.16     319 1456.33   340.7 1464.45   362.9 1470.52   369.9 1472.82
#Mann= 4 ,-1,0
       0     .05       0   145.6    .045       0   164.4     .05       0
     310     .06       0
Bank Sta=145.6,164.4
XS Rating Curve= 0 ,0
Exp/Cntr(USF)=0,0
Exp/Cntr=0.3,0.1

Type RM Length L Ch R = 1 ,8521    ,277.9,276.7,269.6
XS GIS Cut Line= 3
2193275.51529216717195.8486897652193505.60149481717371.289419288
2193548.74265781717405.802349686
#Sta/Elev= 30
       0 1448.23    15.9 1442.26      26 1439.35    41.1 1434.23    52.8 1430.76
    56.2 1429.97    72.8 1428.42   107.7 1426.66   136.6 1424.68   160.5 1424.28
   165.9 1423.06   171.9 1421.57   176.9 1421.31   181.2 1421.96   187.1 1423.48
   192.6  1423.8     202  1423.1   206.7 1423.73   212.6 1425.49   217.1  1426.2
   232.6 1426.29   237.2 1426.97   242.3 1428.96   247.3 1430.33     264 1430.74
   272.5 1431.41   292.5 1433.99   313.1 1436.14   337.2 1439.14   344.6 1442.49
#Mann= 6 ,-1,0
       0     .05       0   165.9    .045       0   187.1     .05       0
     210     .06       0  309.34     .07       0  339.34      .1       0
Bank Sta=165.9,187.1
XS Rating Curve= 0 ,0
Exp/Cntr(USF)=0,0
Exp/Cntr=0.3,0.1

Type RM Length L Ch R = 1 ,8245    ,155.7,154.4,152.9
XS GIS Cut Line= 2
2193126.91795294717443.1913576182193441.36909657717553.440996389
#Sta/Elev= 30
       0 1446.38     2.5 1445.71     5.6  1445.2    15.1 1444.56    22.5 1442.53
      31 1441.53    43.3 1438.39    49.6  1437.2    73.4 1434.04     103  1427.6
   111.5 1424.33   115.5 1423.18   119.71422.327   124.3 1421.04   128.5 1420.58
   131.2 1420.96   135.9 1422.11   137.5 1422.46   153.2 1423.43   190.8 1425.11
   200.6 1425.43     226 1425.79   238.7 1426.92   250.5 1427.58     298 1432.21
   306.5 1433.62   310.8 1434.03   327.7 1434.53     332 1436.18333.2184 1436.98
#Mann= 3 ,-1,0
       0     .05       0   119.7    .045       0   135.9     .05       0
Bank Sta=119.7,135.9
XS Rating Curve= 0 ,0
Exp/Cntr(USF)=0,0
Exp/Cntr=0.3,0.1

Type RM Length L Ch R = 1 ,8090    ,447.4,459.4,434.7
XS GIS Cut Line= 2
2193015.01613673 717588.188156952193411.00100259717680.243679273
#Sta/Elev= 30
       0 1431.27     5.1 1430.27    13.5 1429.19    25.1 1426.87    29.9  1426.2
    39.7 1425.53    62.8 1424.46    75.1 1424.03    87.4 1423.82   108.4  1422.3
   124.4 1421.83   140.8 1421.64   165.1 1422.29   181.9 1423.03   194.2 1423.16
   206.5 1423.01   210.6 1422.05   214.7 1420.78   218.8 1420.35   227.1 1422.04
     235 1422.65   251.7 1422.91   284.5 1424.13   313.3  1424.2   321.5 1424.04
   328.3 1424.33   370.8 1427.36   385.5 1428.26   396.2 1429.48   406.5 1431.46
#Mann= 5 ,-1,0
       0     .06       0      40     .05       0   210.6    .045       0
   227.1     .05       0     400      .1       0
Bank Sta=210.6,227.1
XS Rating Curve= 0 ,0
Exp/Cntr(USF)=0,0
Exp/Cntr=0.3,0.1

Type RM Length L Ch R = 1 ,7631    ,223.4,223.4,216.2
XS GIS Cut Line= 2
2193099.13027425 717928.761719782193435.84138163717725.540841051
#Sta/Elev= 30
       0 1440.87    29.6 1435.25    47.9 1431.01    58.7  1428.9    70.4 1427.33
    87.9    1426      90 1425.69    99.8 1423.26   105.3  1422.3   111.2 1421.96
   122.8 1422.22   130.8 1421.95   140.3 1422.13   157.8 1421.91   164.7 1421.58
   169.3 1420.56   174.1 1419.53   178.8 1419.84     185 1420.88   192.8 1422.06
   227.7 1421.56   286.2 1422.57   297.6 1423.12   308.8 1422.87   314.2 1423.02
   328.3 1424.05   341.3 1426.02   370.5 1428.88   385.1 1430.88 393.285 1432.32
#Mann= 4 ,-1,0
       0     .05       0   169.3    .045       0     185     .05       0
     290      .1       0
Bank Sta=169.3,185
XS Rating Curve= 0 ,0
Exp/Cntr(USF)=0,0
Exp/Cntr=0.3,0.1

Type RM Length L Ch R = 1 ,7408    ,252.8,259.5,247
XS GIS Cut Line= 2
2193297.50464391718052.3053780352193486.36706859717814.549635293
#Sta/Elev= 30
       0 1446.18    24.4 1441.65    29.5  1440.5    35.4  1438.8    42.9 1437.66
    49.7 1436.22    62.2 1432.22    68.6 1429.91    83.8  1423.4    85.7 1422.74
    89.41421.939    95.2 1421.35   131.7 1420.84   135.1 1420.27   139.3 1419.44
     147 1419.07     155 1420.44   162.4 1421.17   166.4 1421.23   208.3 1420.82
   228.8  1421.2   235.8 1422.04     249 1424.93   274.4 1427.91   280.8 1428.39
     285 1427.98   288.8 1427.35   291.7 1427.32   295.2 1427.64303.6393 1429.17
#Mann= 4 ,-1,0
       0     .05       0   135.1    .045       0     155     .05       0
     230      .1       0
Bank Sta=135.1,155
XS Rating Curve= 0 ,0
Exp/Cntr(USF)=0,0
Exp/Cntr=0.3,0.1

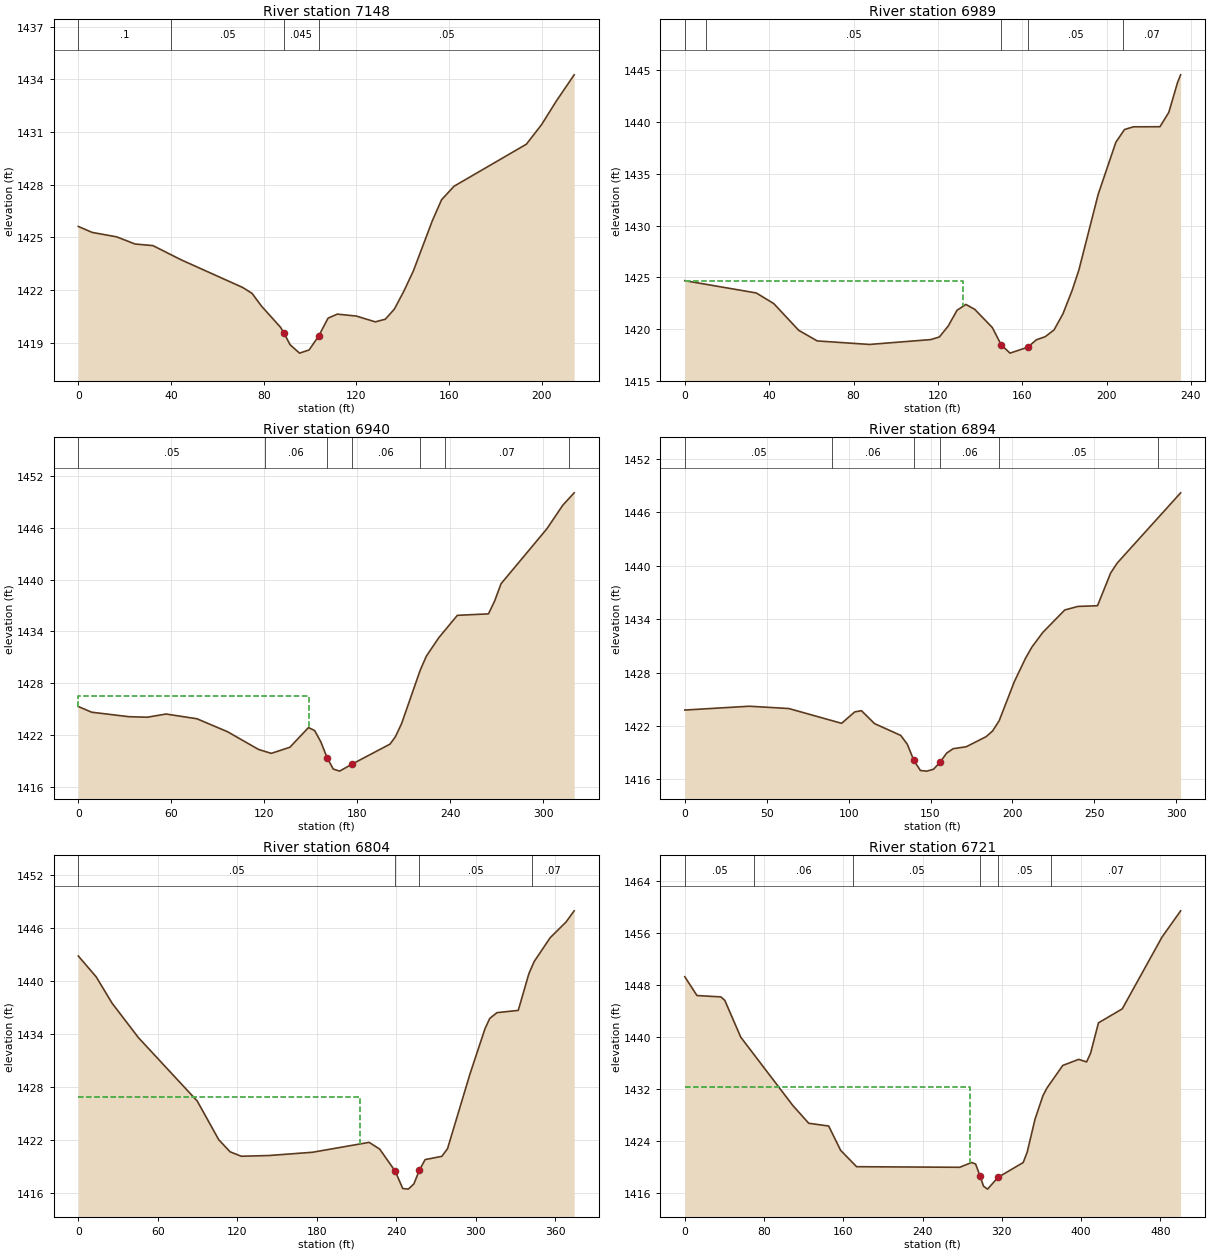
Type RM Length L Ch R = 1 ,7148    ,145.5,158.9,168.5
XS GIS Cut Line= 4
 2193518.1726924718069.7533442432193556.82863157718023.938716179
2193577.46203099717927.2055922672193620.17178236717892.261250239
#Sta/Elev= 30
       0 1425.62       6 1425.28    16.5 1425.03    24.5 1424.62    32.2 1424.53
    44.4 1423.72    70.9 1422.15      75 1421.81    79.1 1421.08    87.3 1419.88
    88.7 1419.57    91.4 1418.89    95.5 1418.41    99.6 1418.59   103.7 1419.37
   107.8  1420.4   111.8 1420.63     120 1420.52   128.2 1420.19   132.5 1420.34
   136.4 1420.91   140.5 1421.93   144.6 1423.08   152.8 1425.94   156.8 1427.14
   162.2 1427.91   193.4  1430.3     200 1431.42   206.3 1432.75214.0367 1434.25
#Mann= 4 ,-1,0
       0      .1       0      40     .05       0    88.7    .045       0
   103.7     .05       0
Bank Sta=88.7,103.7
XS Rating Curve= 0 ,0
Exp/Cntr(USF)=0,0
Exp/Cntr=0.3,0.1

Type RM Length L Ch R = 1 ,6989    ,46.9,49.6,52.4
XS GIS Cut Line= 3
2193539.37202686718066.2802680222193653.39708314718036.566898308
2193765.56505381718002.396523136
#Sta/Elev= 30
       0 1424.67    33.9 1423.48    42.2 1422.45      54 1419.87    62.8 1418.84
    87.6  1418.5   116.6 1418.97   120.7 1419.22   124.9 1420.28   129.1 1421.81
   133.3 1422.37   137.5 1421.89   145.8 1420.14     150 1418.47   154.2 1417.66
   162.6 1418.23   166.7 1418.95   170.9 1419.25   175.1 1419.91   179.3 1421.46
   183.7 1423.75   186.9 1425.73     196 1433.01   204.4 1438.06   208.5 1439.29
   212.7 1439.55   225.3 1439.56   229.5 1440.95   233.6 1443.81   235.1 1444.58
#Mann= 5 ,-1,0
       0      .1       0      10     .05       0     150    .045       0
   162.6     .05       0  207.83     .07       0
#XS Ineff= 2 , 0
        132.03521424.653
Permanent Ineff=
       T       F
Bank Sta=150,162.6
XS Rating Curve= 0 ,0
Exp/Cntr(USF)=0,0
Exp/Cntr=0.3,0.1

Type RM Length L Ch R = 1 ,6940    ,45.6,45.7,46.1
XS GIS Cut Line= 4
2193519.62346828718075.0191449032193629.95316818 718077.28701116
2193745.94312631718071.3691561532193839.44523541718066.634872148
#Sta/Elev= 30
       0 1425.28     8.6 1424.62    32.6  1424.1    44.6 1424.04    56.6 1424.41
    76.6 1423.86    96.4 1422.35   116.4  1420.3   124.6 1419.85   136.6 1420.56
   148.6 1422.84   152.6 1422.49   156.6 1421.17   160.6 1419.35   164.6 1418.03
   168.7 1417.79   176.7  1418.6   201.2 1420.92   204.7 1421.77   208.7  1423.3
   220.7 1429.48   224.7 1431.12   232.7 1433.25   244.7 1435.85   264.8 1436.02
   268.8 1437.52   272.9 1439.51   302.5 1445.88   312.8 1448.62320.1157 1450.05
#Mann= 7 ,-1,0
       0     .05       0  120.35     .06       0   160.6    .045       0
   176.7     .06       0  220.35     .05       0  236.49     .07       0
  316.49     .06       0
#XS Ineff= 2 , 0
          149.07 1426.46
Permanent Ineff=
       F       F
Bank Sta=160.6,176.7
XS Rating Curve= 0 ,0
Exp/Cntr(USF)=0,0
Exp/Cntr=0.3,0.1

Type RM Length L Ch R = 1 ,6894    ,95.4,89.8,88.9
XS GIS Cut Line= 4
 2193553.0210531718108.0598571942193664.27672722718119.895567207
2193770.79811734718115.1612832022193854.83165843718111.610570198
#Sta/Elev= 30
       0  1423.8    39.4 1424.23    63.5 1423.97    95.7 1422.31   103.7 1423.59
   107.8 1423.73   115.8 1422.28   131.8 1420.95   135.8 1419.96   139.8 1418.15
   143.8 1417.01   147.8 1416.94   151.8 1417.15   155.8 1417.94   159.8 1418.96
   163.8 1419.46   171.8 1419.68   183.9 1420.81   187.9 1421.46   191.9 1422.61
   201.1 1426.98   207.9  1429.6   211.9 1430.89   218.5 1432.52   231.9 1435.04
   239.9 1435.44   251.9 1435.52   259.9 1439.19   263.9 1440.31302.6185  1448.2
#Mann= 6 ,-1,0
       0     .05       0      90     .06       0   139.8    .045       0
   155.8     .06       0  191.88     .05       0  288.51      .1       0
Bank Sta=139.8,155.8
XS Rating Curve= 0 ,0
Exp/Cntr(USF)=0,0
Exp/Cntr=0.3,0.1

Type RM Length L Ch R = 1 ,6804    ,78,83.1,87.4
XS GIS Cut Line= 5
2193510.74865376718249.191994292 2193606.4043514718240.247390608
 2193683.7469059 718217.17512243 2193802.8692077718176.571034023
2193874.24221869718170.128953715
#Sta/Elev= 30
       0 1442.82    13.5 1440.46    25.5 1437.48    45.4 1433.58    89.8 1426.41
     106 1422.04   114.6 1420.67     123 1420.17   143.8 1420.25   176.8 1420.62
   219.5 1421.74   227.5 1420.98   239.21418.484   244.9 1416.52   249.1 1416.45
   253.3 1417.04   257.5 1418.61   261.8 1419.79   274.4 1420.16   278.7 1421.02
   295.6 1429.45     307  1434.6   310.6 1435.76     316 1436.41   332.1 1436.67
   340.1 1440.81   344.1 1442.19   356.2 1444.89   368.2 1446.67   374.3 1447.93
#Mann= 4 ,-1,0
       0     .05       0   239.2    .045       0   257.5     .05       0
  342.64     .07       0
#XS Ineff= 2 , 0
          212.73 1426.87
Permanent Ineff=
       T       F
Bank Sta=239.2,257.5
XS Rating Curve= 0 ,0
Exp/Cntr(USF)=0,0
Exp/Cntr=0.3,0.1

Type RM Length L Ch R = 1 ,6721    ,156.1,160.1,154.7
XS GIS Cut Line= 3
2193472.06276983718294.605255985 2193650.0738752718272.576226375
2193971.08200218718271.226955433
#Sta/Elev= 30
       0 1449.32    12.3 1446.43    36.4 1446.22    40.4 1445.68    56.5 1440.02
     109 1429.52   125.1 1426.78   145.2 1426.36   157.3 1422.61   173.4  1420.1
   277.5 1420.01   289.5 1420.75   293.5 1420.51   298.11418.621   301.5  1417.1
   305.5 1416.65   316.3 1418.48   341.5 1420.74   345.5 1422.31   353.5 1427.43
   361.5 1431.04   365.5 1432.21   381.5 1435.68   397.5 1436.61   405.5 1436.22
   409.5 1437.55   417.5 1442.23   441.5 1444.38   481.5 1455.39   500.4 1459.46
#Mann= 6 ,-1,0
       0     .05       0      70     .06       0     170     .05       0
   298.1    .045       0   316.3     .05       0  369.37     .07       0
#XS Ineff= 2 , 0
             288 1432.42
Permanent Ineff=
       T       F
Bank Sta=298.1,316.3
XS Rating Curve= 0 ,0
Exp/Cntr(USF)=0,0
Exp/Cntr=0.3,0.1

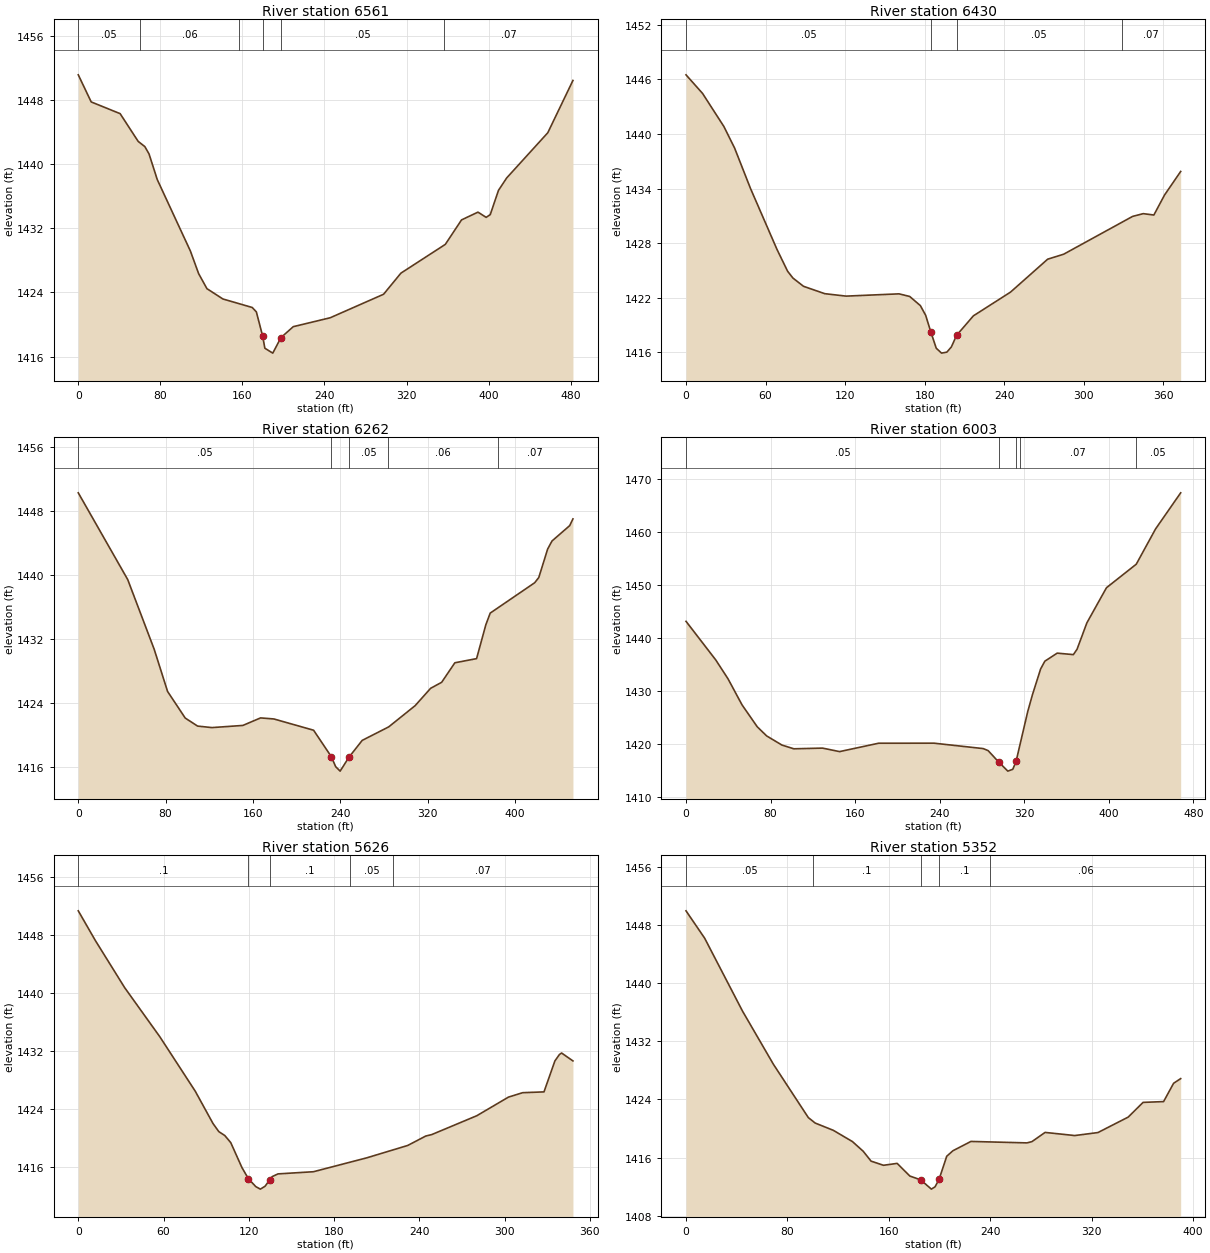
Type RM Length L Ch R = 1 ,6561    ,129.1,130.7,133
XS GIS Cut Line= 3
2193483.71088384718349.7396622962193629.47973978 718331.92047638
2193964.74989732 718340.54870898
#Sta/Elev= 30
       0 1451.14    12.6 1447.76    40.8  1446.3    58.4 1442.84    64.9 1442.19
      69 1441.27      77 1438.08   109.3 1429.17   117.3 1426.36   125.4 1424.48
     141 1423.19   169.6 1422.13   173.6 1421.58   179.71418.579   181.9 1417.05
   189.6 1416.44   197.6 1418.38   209.6 1419.74   245.6 1420.85   297.6 1423.78
   314.5 1426.41   357.8    1430   373.6 1433.05   389.6 1434.02   397.6 1433.37
   401.6 1433.71   409.6 1436.73   417.6 1438.28   457.7 1443.92   482.2 1450.44
#Mann= 6 ,-1,0
       0     .05       0      60     .06       0  156.85     .05       0
   179.7    .045       0   197.6     .05       0  356.85     .07       0
Bank Sta=179.7,197.6
XS Rating Curve= 0 ,0
Exp/Cntr(USF)=0,0
Exp/Cntr=0.3,0.1

Type RM Length L Ch R = 1 ,6430    ,166.4,168.3,168.5
XS GIS Cut Line= 3
2193511.66635746718461.5615567862193670.08070799718453.796147446
2193884.40600576718447.583819975
#Sta/Elev= 30
       0 1446.51    12.5 1444.46    28.5 1440.84    36.6 1438.47    48.6 1434.02
    68.6 1427.31    76.6 1424.91    80.6 1424.16    88.6 1423.25   104.6 1422.44
   120.7 1422.17   160.7 1422.42   168.7 1422.13   176.7 1421.13   180.7 1420.07
   184.7 1418.19   188.7 1416.44   192.7  1415.9   196.7 1416.01   200.1 1416.58
     204 1417.85   216.7    1420   244.7 1422.61   272.7 1426.23   284.8 1426.78
   336.8 1430.94   344.8 1431.24   352.8 1431.09   360.8 1433.28373.0199 1435.88
#Mann= 4 ,-1,0
       0     .05       0   184.7    .045       0     204     .05       0
   328.6     .07       0
Bank Sta=184.7,204
XS Rating Curve= 0 ,0
Exp/Cntr(USF)=0,0
Exp/Cntr=0.3,0.1

Type RM Length L Ch R = 1 ,6262    ,244.2,258.5,267.8
XS GIS Cut Line= 3
2193463.57237594718567.5105430912193635.22051786718597.084460577
2193911.11091826718638.627802723
#Sta/Elev= 30
       0 1450.29    45.3 1439.45    69.6 1430.72    81.8 1425.47      98 1422.14
   109.3 1421.14   122.4 1420.95   150.8 1421.22     167 1422.16   179.2 1422.03
   215.6 1420.62   231.8 1417.32   235.8 1416.07   239.9 1415.51     248 1417.25
   260.1 1419.35   284.4 1421.04   308.6 1423.69   322.8 1425.86   332.9 1426.61
     345 1429.05   364.9 1429.57   373.4 1433.81   377.4 1435.26   418.1 1439.05
   421.9 1439.71     430 1443.26     434 1444.27   450.2 1446.19453.1779 1447.03
#Mann= 5 ,-1,0
       0     .05       0   231.8    .045       0     248     .05       0
  284.18     .06       0  384.18     .07       0
Bank Sta=231.8,248
XS Rating Curve= 0 ,0
Exp/Cntr(USF)=0,0
Exp/Cntr=0.3,0.1

Type RM Length L Ch R = 1 ,6003    ,371.4,377.6,379.3
XS GIS Cut Line= 4
2193444.80024481718663.0188668452193640.54658737718794.149032295
2193746.00276358718968.844112088 2193761.9809721718992.278817914
#Sta/Elev= 30
       0 1443.19    28.1 1435.92    39.8 1432.33      53 1427.44    67.4  1423.3
    76.3 1421.58    90.7 1419.86     102 1419.15   129.2 1419.28   145.3 1418.62
   182.2  1420.2   234.6 1420.21   281.2 1419.19   285.9  1418.8   295.8 1416.66
   304.5 1414.94   309.2 1415.29   312.3 1416.78   323.3 1426.16   327.8 1429.36
   335.5  1434.2   339.5 1435.67   351.2 1437.19   366.5 1436.91     370 1437.93
   379.3 1442.91   397.8 1449.52     426 1453.96   444.3 1460.62468.0301 1467.42
#Mann= 5 ,-1,0
       0     .05       0   295.8    .045       0   312.3     .05       0
  315.61     .07       0  425.61     .05       0
Bank Sta=295.8,312.3
XS Rating Curve= 0 ,0
Exp/Cntr(USF)=0,0
Exp/Cntr=0.3,0.1

Type RM Length L Ch R = 1 ,5626    ,280.3,273.6,266.6
XS GIS Cut Line= 3
2193294.90197447718745.495470055 2193309.7747083718804.986405378
2193388.19457759719080.808014606
#Sta/Elev= 30
       0 1451.36      12 1447.27    32.7 1440.75    57.4 1433.99    82.3 1426.49
    94.8 1422.03    98.9 1420.91   103.1 1420.37   107.3 1419.39   115.2 1415.94
   119.7 1414.42   124.9 1413.33   128.1 1412.98   131.4 1413.37   134.7 1414.25
   136.4  1414.7   140.5 1415.08   165.5 1415.38   202.9 1417.29   231.8    1419
   244.5  1420.3   248.7  1420.5   280.4  1423.1   302.7 1425.67   312.7 1426.28
   327.7 1426.39   335.4 1430.67   338.6 1431.55   340.1 1431.75348.0748 1430.66
#Mann= 5 ,-1,0
       0      .1       0   119.7    .045       0   134.7      .1       0
  191.32     .05       0  221.32     .07       0
Bank Sta=119.7,134.7
XS Rating Curve= 0 ,0
Exp/Cntr(USF)=0,0
Exp/Cntr=0.3,0.1

Type RM Length L Ch R = 1 ,5352    ,231.1,242.4,245.4
XS GIS Cut Line= 2
2192972.56927035718895.3044617332193262.18196004719156.929370486
#Sta/Elev= 30
       0 1449.94    14.7 1446.18    44.6 1436.14      69 1428.82    96.5  1421.5
   101.9 1420.75   116.2 1419.75   131.3  1418.2   139.8 1416.87     146 1415.51
   155.8 1414.94   166.6  1415.2   176.6 1413.46   185.1 1412.94   193.6 1411.66
   196.5 1411.98   199.7 1413.02   205.7 1416.18   210.6 1416.94   224.8 1418.22
     269 1418.02   272.9 1418.19   283.3 1419.46   306.7 1419.03     325 1419.44
   348.9 1421.57   360.6 1423.59   376.8  1423.7   384.7 1426.22390.2859 1426.86
#Mann= 5 ,-1,0
       0     .05       0     100      .1       0   185.1    .045       0
   199.7      .1       0     240     .06       0
Bank Sta=185.1,199.7
XS Rating Curve= 0 ,0
Exp/Cntr(USF)=0,0
Exp/Cntr=0.3,0.1

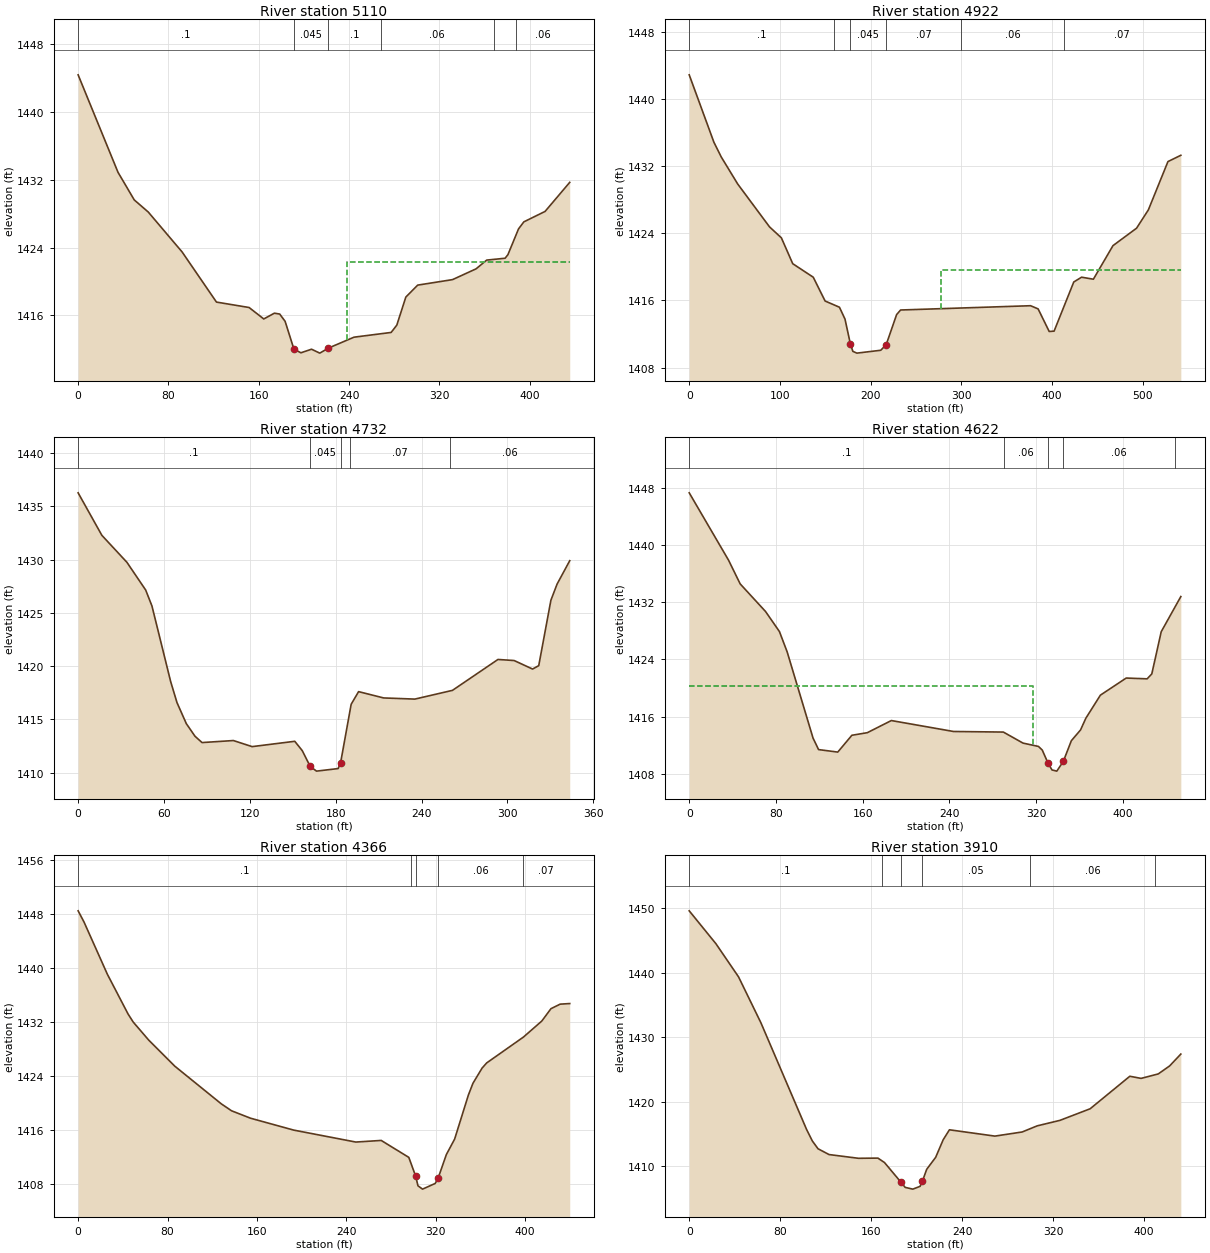
Type RM Length L Ch R = 1 ,5110    ,180,187.6,186.1
XS GIS Cut Line= 3
2192854.45525678719026.1141789262192896.76949603719091.581492488
2193084.38923612719395.764985991
#Sta/Elev= 30
       0 1444.38    35.3 1432.89    49.7 1429.63    62.1  1428.2    92.1 1423.49
   122.5 1417.58   151.4 1416.94   164.4 1415.59   173.8 1416.27   178.5 1416.17
   183.3 1415.31   191.1 1412.03   197.3  1411.6   206.7 1412.02     214 1411.56
   221.6 1412.15   244.3 1413.44   277.2    1414   282.2 1414.86   290.2 1418.17
   300.7 1419.58   331.6 1420.23   352.4  1421.5   361.8 1422.53   378.1 1422.75
   380.6 1423.17     390 1426.21   394.7 1427.04   413.5 1428.27435.3433  1431.7
#Mann= 6 ,-1,0
       0      .1       0   191.1    .045       0   221.6      .1       0
  267.95     .06       0  367.95     .07       0  387.95     .06       0
#XS Ineff= 2 , 0
                          237.75         1422.36
Permanent Ineff=
       F       T
Bank Sta=191.1,221.6
XS Rating Curve= 0 ,0
Exp/Cntr(USF)=0,0
Exp/Cntr=0.3,0.1

Type RM Length L Ch R = 1 ,4922    ,187.2,190.6,184.5
XS GIS Cut Line= 3
2192730.46731857719108.2938482872192857.50750682 719394.13427185
2193069.33080554719481.540089558
#Sta/Elev= 30
       0 1442.89    27.2 1434.86    35.3  1433.1    53.5 1429.87    88.5 1424.77
   101.6 1423.46   114.1 1420.38   136.7 1418.77   149.8 1415.93   165.6 1415.19
   171.7 1413.78   177.7 1410.79   180.4 1409.93   184.8 1409.72   211.1 1410.06
   217.1 1410.72   228.6 1414.31     233 1414.86   376.3 1415.37   384.6 1414.99
   396.8  1412.3   402.2 1412.34   423.9  1418.2   432.5 1418.77   445.5 1418.53
   467.1 1422.53   493.1 1424.61   506.1 1426.79   527.7 1432.55   541.9  1433.3
#Mann= 6 ,-1,0
       0      .1       0     160     .07       0   177.7    .045       0
   217.1     .07       0     300     .06       0   412.8     .07       0
#XS Ineff= 2 , 0
                          277.86         1419.62
Permanent Ineff=
       F       F
Bank Sta=177.7,217.1
XS Rating Curve= 0 ,0
Exp/Cntr(USF)=0,0
Exp/Cntr=0.3,0.1

Type RM Length L Ch R = 1 ,4732    ,121.6,109.8,99.3
XS GIS Cut Line= 3
2192579.56533666719214.0145635762192690.94453619719465.357004984
2192715.58595201719529.424686127
#Sta/Elev= 30
       0 1436.27    16.6 1432.28    34.1 1429.75    47.2 1427.15    51.6 1425.65
    64.7 1418.54    69.1 1416.58    75.6 1414.61    81.7 1413.42    86.6 1412.83
   108.5 1413.02   121.6 1412.45   151.4 1412.95   156.6 1412.08   162.2 1410.59
   166.6 1410.15   181.7 1410.39   183.41410.912   190.8 1416.42     196 1417.61
   213.5 1417.02   235.3 1416.91   261.6 1417.73   293.4 1420.63   304.7 1420.53
   317.6 1419.73   321.9 1420.05   330.4 1426.19   334.7  1427.7343.5582  1429.9
#Mann= 5 ,-1,0
       0      .1       0   162.2    .045       0   183.4      .1       0
     190     .07       0     260     .06       0
Bank Sta=162.2,183.4
XS Rating Curve= 0 ,0
Exp/Cntr(USF)=0,0
Exp/Cntr=0.3,0.1

Type RM Length L Ch R = 1 ,4622    ,239.8,255.6,275.1
XS GIS Cut Line= 4
2192339.72387356719266.552777207 2192565.6566264719450.900707701
2192652.17537529719493.6124951292192677.36437813719553.847067144
#Sta/Elev= 30
       0 1447.29    36.3 1437.87      47 1434.56    70.4  1430.7    83.2  1427.9
    90.3 1425.07   114.2 1413.01   119.3  1411.4     137 1411.05     150  1413.4
   164.2 1413.76   186.4 1415.46   243.8 1413.93   289.7 1413.85   307.8 1412.31
   322.1 1411.84   325.6 1411.33     331 1409.47   334.6 1408.55     339 1408.39
     345 1409.75   352.4 1412.64   360.9 1414.15   365.8 1415.79   379.2 1419.01
     403  1421.4   422.3 1421.29   426.6 1421.98   435.3 1427.88453.3752 1432.79
#Mann= 5 ,-1,0
       0      .1       0     290     .06       0     331    .045       0
     345     .06       0  448.09     .05       0
#XS Ineff= 2 , 0
           316.9 1420.35
Permanent Ineff=
       T       F
Bank Sta=331,345
XS Rating Curve= 0 ,0
Exp/Cntr(USF)=0,0
Exp/Cntr=0.3,0.1

Type RM Length L Ch R = 1 ,4366    ,467.2,456.6,441.4
XS GIS Cut Line= 3
2192271.66789768719290.584955834 2192406.7393622719521.788363568
2192368.34580018719689.574636136
#Sta/Elev= 30
       0 1448.42     5.2 1446.79    26.2 1439.02    44.7 1433.14    49.3 1431.95
    63.2 1429.27    86.4 1425.43   128.1 1419.84   137.3 1418.81   154.3 1417.71
   192.9 1415.95   248.5 1414.18   271.2 1414.42   295.9 1411.91     3021409.144
   304.1  1407.7   308.2 1407.21   319.5 1408.05   322.1 1408.83   329.5 1412.33
   336.9 1414.62   349.2 1421.14   353.3 1422.89   361.5 1425.14   365.6  1425.9
   398.5 1429.73   414.9  1432.1   423.1 1433.93   431.3  1434.6439.8902 1434.69
#Mann= 5 ,-1,0
       0      .1       0  297.77     .06       0     302    .045       0
   322.1     .06       0  397.77     .07       0
Bank Sta=302,322.1
XS Rating Curve= 0 ,0
Exp/Cntr(USF)=0,0
Exp/Cntr=0.3,0.1

Type RM Length L Ch R = 1 ,3910    ,184.4,186.6,188.4
XS GIS Cut Line= 2
2191986.65223481719418.3552601082192245.07799408719765.118414513
#Sta/Elev= 30
       0 1449.61    23.5 1444.51    43.4 1439.37    63.1 1432.24   103.3 1415.69
   108.3 1413.93   113.3 1412.72     123 1411.82   148.9 1411.24     166 1411.27
   171.8 1410.58     186 1407.59     190 1406.73   196.7 1406.46   203.1 1406.89
   205.11407.676   208.9 1409.53   216.8 1411.39   223.4 1414.11   228.9 1415.66
   268.9 1414.68   292.9 1415.32   306.1 1416.27   326.1 1417.12   352.7 1418.92
   387.6 1423.96   397.5 1423.63   412.6 1424.32   422.6 1425.56 432.468  1427.4
#Mann= 6 ,-1,0
       0      .1       0     170     .05       0     186    .045       0
   205.1     .05       0     300     .06       0     410     .07       0
Bank Sta=186,205.1
XS Rating Curve= 0 ,0
Exp/Cntr(USF)=0,0
Exp/Cntr=0.3,0.1

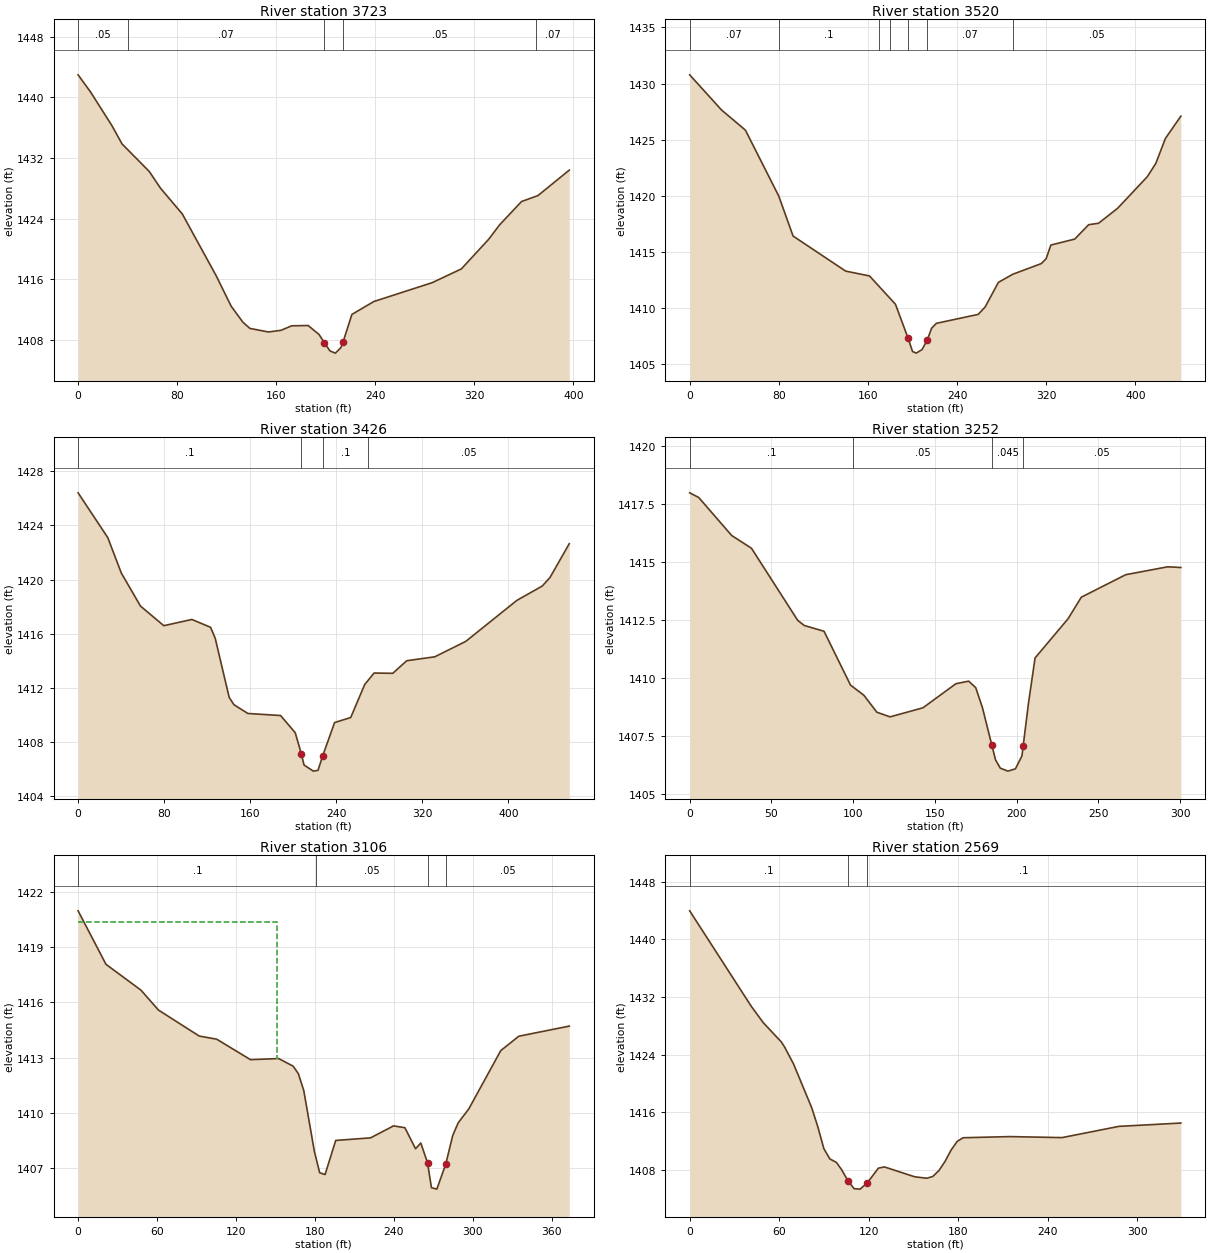
Type RM Length L Ch R = 1 ,3723    ,201.9,202.8,203.7
XS GIS Cut Line= 2
2191883.89516471719512.9999299412192052.43950303719872.048276534
#Sta/Elev= 30
       0 1442.96    10.1 1440.69    27.4 1436.24    35.5 1433.85    57.5 1430.22
    66.5 1428.03    84.2 1424.61   111.6 1416.45   123.6 1412.47     133 1410.37
   138.7 1409.54   153.7 1409.07   163.7 1409.28   172.5 1409.88   185.8 1409.92
   194.6 1408.73   198.8 1407.66   203.5 1406.56   207.8 1406.28   212.3 1407.03
   213.9 1407.71   221.1 1411.38   238.8 1413.08     286 1415.57   309.5 1417.38
   331.6 1421.29   340.4 1423.19   358.1 1426.26   371.4 1427.05396.6395  1430.4
#Mann= 5 ,-1,0
       0     .05       0      40     .07       0   198.8    .045       0
   213.9     .05       0     370     .07       0
Bank Sta=198.8,213.9
XS Rating Curve= 0 ,0
Exp/Cntr(USF)=0,0
Exp/Cntr=0.3,0.1

Type RM Length L Ch R = 1 ,3520    ,94.1,94.3,93.1
XS GIS Cut Line= 2
2191708.23294189719578.4941170062191866.13513449719990.104326936
#Sta/Elev= 30
       0 1430.78    28.6 1427.65      50 1425.86      80 1419.98    92.8 1416.43
     140 1413.31   161.4 1412.88   184.7 1410.36   196.11407.322     200 1406.16
   203.3 1406.01   208.5 1406.32   213.3 1407.19   217.1 1408.22   221.4 1408.66
     259 1409.46   265.2 1410.12   277.1 1412.31     290 1413.03   315.6 1413.98
   319.9 1414.41   324.2 1415.63   345.6 1416.16   358.1 1417.44     367 1417.57
   384.2 1418.91   410.8 1421.72   418.4  1422.9     427 1425.12440.8583  1427.1
#Mann= 7 ,-1,0
       0     .07       0      80      .1       0     170     .06       0
     180     .07       0   196.1    .045       0   213.3     .07       0
     290     .05       0
Bank Sta=196.1,213.3
XS Rating Curve= 0 ,0
Exp/Cntr(USF)=0,0
Exp/Cntr=0.3,0.1

Type RM Length L Ch R = 1 ,3426    ,170.3,174.1,176.2
XS GIS Cut Line= 2
2191608.87875328719599.7843002792191787.18403819720020.265419905
#Sta/Elev= 30
       0 1426.41    27.6  1423.1    40.2 1420.48      58 1418.04    79.7 1416.59
   105.8 1417.05   123.2 1416.47   127.5 1415.66   140.5 1411.29   144.9 1410.75
   157.9  1410.1   188.3 1409.95   201.9 1408.68   207.6 1407.12   210.1 1406.29
   218.8 1405.84   223.1  1405.9   227.4 1406.96   238.5 1409.43   253.5  1409.8
   266.5 1412.24   275.2 1413.09   292.6 1413.07   305.6    1414   331.7 1414.29
   360.5 1415.43     408 1418.46   431.6 1419.52   438.8 1420.15456.7244 1422.65
#Mann= 4 ,-1,0
       0      .1       0   207.6    .045       0   227.4      .1       0
     270     .05       0
Bank Sta=207.6,227.4
XS Rating Curve= 0 ,0
Exp/Cntr(USF)=0,0
Exp/Cntr=0.3,0.1

Type RM Length L Ch R = 1 ,3252    ,141.6,146.4,148.3
XS GIS Cut Line= 3
 2191505.9762008719647.6872126412191542.34693056719920.911231301
 2191548.3752552719945.067119969
#Sta/Elev= 30
       0    1418     5.5  1417.8    25.7 1416.16    37.8 1415.61    66.1  1412.5
    70.1 1412.28    82.2 1412.03    98.4 1409.71   106.6 1409.27   114.5 1408.54
   122.6 1408.34   142.7 1408.73   162.9 1409.77   170.7 1409.88     175  1409.6
   179.1 1408.74   184.9 1407.11   187.1 1406.49     190 1406.13   194.7    1406
   199.3  1406.1   203.3 1406.66     204 1407.07   207.3 1408.94   211.3 1410.88
   231.5 1412.57   239.6  1413.5   266.8 1414.47   292.4 1414.81   300.5 1414.78
#Mann= 4 ,-1,0
       0      .1       0     100     .05       0   184.9    .045       0
     204     .05       0
Bank Sta=184.9,204
XS Rating Curve= 0 ,0
Exp/Cntr(USF)=0,0
Exp/Cntr=0.3,0.1

Type RM Length L Ch R = 1 ,3106    ,555.2,536.1,511.9
XS GIS Cut Line= 4
2191466.43148187719582.0676205132191414.19168032719691.475506773
2191383.24206205719887.522611071 2191408.0806092719935.228392107
#Sta/Elev= 30
       0 1420.97    21.2 1418.07    47.8 1416.67    61.1 1415.59    92.1 1414.18
   105.4 1414.01   131.1  1412.9   152.5 1412.96   163.5 1412.55   167.5 1412.14
   171.6 1411.23   179.7 1407.92   183.7 1406.77   187.8 1406.67   195.9 1408.52
   222.4 1408.66   239.9 1409.31   248.5 1409.21   256.6 1408.07   260.6 1408.38
   265.71407.315   268.7 1405.96   272.8 1405.88   279.5 1407.22   284.9 1408.79
     289 1409.47   297.1 1410.23   321.4 1413.39   335.1 1414.17   373.5 1414.72
#Mann= 4 ,-1,0
       0      .1       0  181.24     .05       0   265.7    .045       0
   279.5     .05       0
#XS Ineff= 2 , 0
        151.6159 1420.36
Permanent Ineff=
       T       F
Bank Sta=265.7,279.5
XS Rating Curve= 0 ,0
Exp/Cntr(USF)=0,0
Exp/Cntr=0.3,0.1

Type RM Length L Ch R = 1 ,2569    ,219.1,212.2,205.1
XS GIS Cut Line= 3
2191043.57261773719930.053086354 2191254.9412068719893.912343145
2191363.72606072719930.102977616
#Sta/Elev= 30
       0 1443.97    41.2 1430.74    49.3 1428.45    61.5 1425.75    63.7 1425.03
    69.6 1422.71    81.8 1416.62    85.8 1414.04    89.9 1410.97    93.9 1409.54
    98.3 1409.06   101.8 1408.05   106.1 1406.48   110.2 1405.41   114.2 1405.35
   119.1 1406.24   126.4 1408.26   130.5 1408.43   150.8 1407.06   158.9 1406.86
   162.9 1407.11     167 1407.93   171.1  1409.2   175.1 1410.76   179.2 1411.97
   183.2 1412.48   214.4 1412.64   249.5  1412.5   287.6 1414.06329.0829 1414.52
#Mann= 3 ,-1,0
       0      .1       0   106.1    .045       0   119.1      .1       0
Bank Sta=106.1,119.1
XS Rating Curve= 0 ,0
Exp/Cntr(USF)=0,0
Exp/Cntr=0.3,0.1