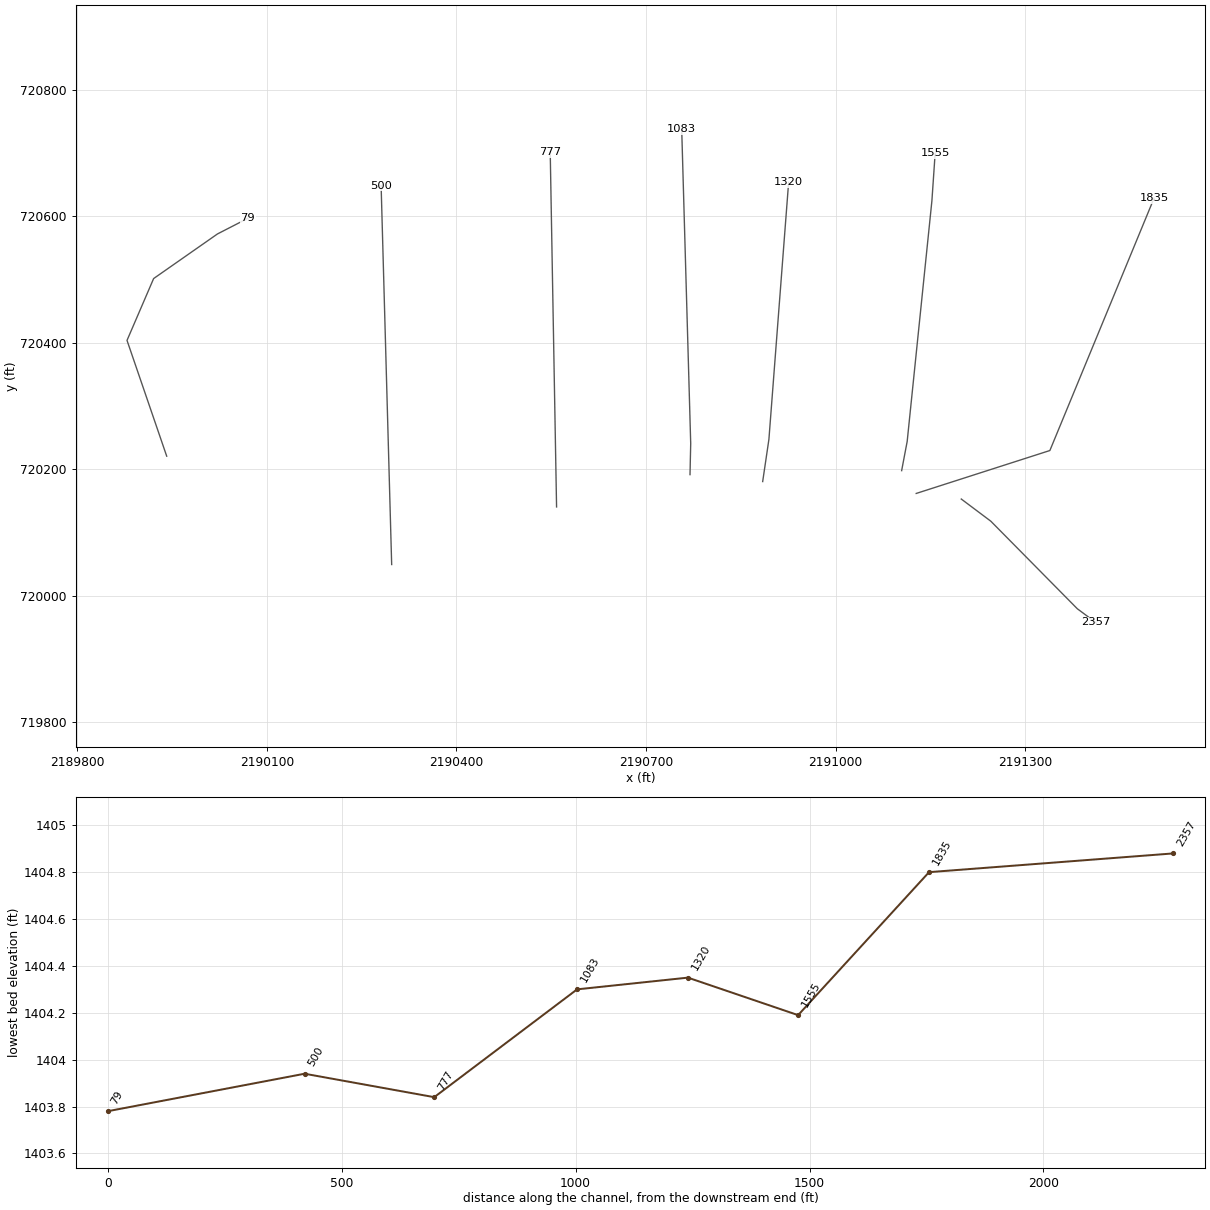
HEC-RAS study LISANDRN.prj: LISANDRN

--- LISANDRN.g01 (geometry) --- (continued)

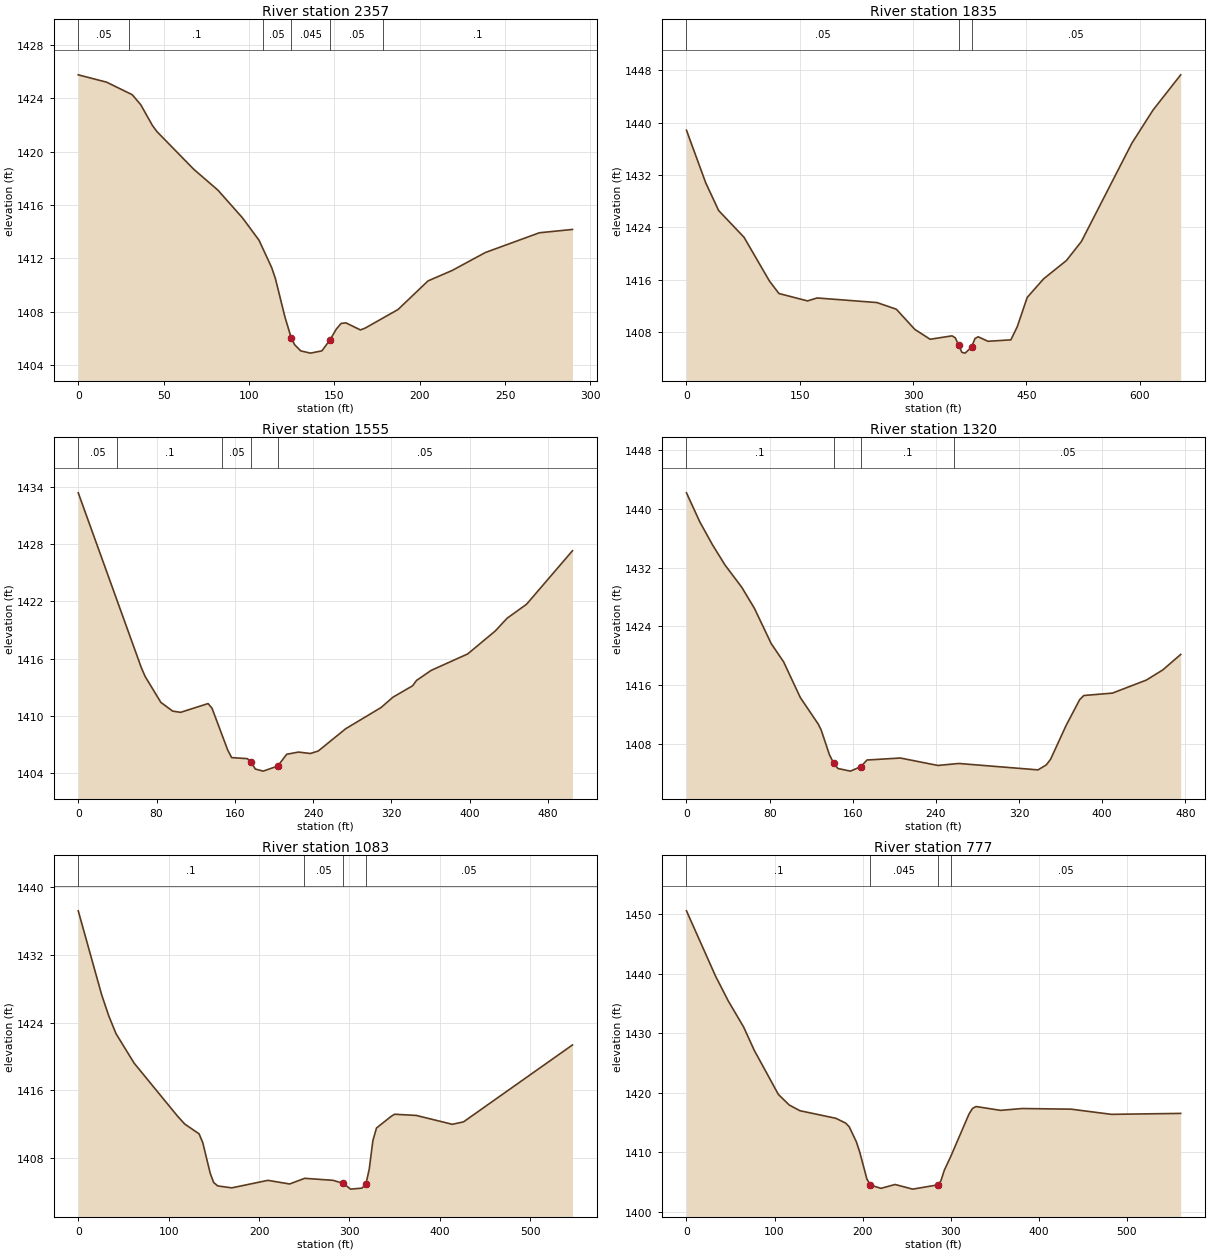
Type RM Length L Ch R = 1 ,2357    ,492.6,522.3,548.3
XS GIS Cut Line= 4
2191198.88586866 720152.829165932191245.62397722 720117.77558451
2191382.49986657719979.2304769952191411.62897308719957.602797676
#Sta/Elev= 30
       0 1425.76    16.6 1425.21    31.6 1424.27    36.6 1423.52    43.5 1421.95
    46.1  1421.5    67.7 1418.67    81.8 1417.11    96.2 1415.03   105.9 1413.35
   113.3  1411.3   115.5 1410.47   121.1 1407.58   124.7 1406.05   126.7 1405.52
   130.3 1405.05     136 1404.88   142.7 1405.05   147.4 1405.86   151.2 1406.69
     154 1407.11   156.8 1407.15   165.3 1406.62   168.1 1406.76   187.3 1408.15
   204.9  1410.3     219 1411.08   238.5 1412.43   270.1 1413.91   289.5 1414.16
#Mann= 6 ,-1,0
       0     .05       0      30      .1       0  108.42     .05       0
   124.7    .045       0   147.4     .05       0  178.42      .1       0
Bank Sta=124.7,147.4
XS Rating Curve= 0 ,0
Exp/Cntr(USF)=0,0
Exp/Cntr=0.3,0.1

Type RM Length L Ch R = 1 ,1835    ,275.7,279.8,282.2
XS GIS Cut Line= 3
2191127.60352888720161.6799304252191339.10019434720229.613201421
2191503.96995005 720628.95748929
#Sta/Elev= 30
       0 1438.86    25.5 1430.82    42.6 1426.59    76.2  1422.5   109.8 1415.82
   122.4 1413.91   160.2 1412.78   172.9 1413.23     252 1412.53   277.8 1411.51
   302.3 1408.42   322.5 1406.92   351.5 1407.44   355.8 1407.14   360.5 1405.99
   364.5 1404.92   368.8  1404.8   377.5 1405.74   381.8 1407.02   386.1  1407.3
   399.1 1406.61   429.4 1406.83     438 1408.88     451 1413.31   472.7 1416.15
     503 1418.96   522.8 1421.87   589.5 1436.87   617.7 1441.97   654.2 1447.33
#Mann= 3 ,-1,0
       0     .05       0   360.5    .045       0   377.5     .05       0
Bank Sta=360.5,377.5
XS Rating Curve= 0 ,0
Exp/Cntr(USF)=0,0
Exp/Cntr=0.3,0.1

Type RM Length L Ch R = 1 ,1555    ,235.9,235.5,237.7
XS GIS Cut Line= 4
2191104.51034238720197.7439200132191113.29254298 720244.05006863
2191152.41325475720624.8782219122191157.54775815720699.930266406
#Sta/Elev= 30
       0  1433.4    64.4 1415.07    68.4 1414.12    84.5  1411.4    96.5 1410.49
   104.6 1410.36   132.7 1411.28   136.7  1410.8   152.8  1406.4   156.8 1405.61
   172.9  1405.5   176.9  1405.1     181 1404.41     189 1404.19   203.9 1404.72
   213.1 1405.96   225.2 1406.19   237.3 1406.04   245.3  1406.3   273.4 1408.64
   309.6 1410.87   321.7 1411.95   341.8 1413.15   345.8 1413.71   360.7 1414.76
   398.1 1416.49   426.4 1418.91   438.3 1420.23   458.3 1421.71   505.2 1427.32
#Mann= 5 ,-1,0
       0     .05       0      40      .1       0  147.13     .05       0
   176.9    .045       0   203.9     .05       0
Bank Sta=176.9,203.9
XS Rating Curve= 0 ,0
Exp/Cntr(USF)=0,0
Exp/Cntr=0.3,0.1

Type RM Length L Ch R = 1 ,1320    ,245.8,236.8,247.7
XS GIS Cut Line= 3
2190884.61594512720180.4767977212190894.47251145720247.282413956
2190925.68657093720654.062283059
#Sta/Elev= 30
       0 1442.15    12.8 1438.21      25  1435.1    37.1 1432.34    53.3  1429.3
    65.4 1426.45    81.5 1421.68    93.5 1419.18   109.5 1414.35   126.8 1410.73
   129.6 1409.93   137.6 1406.55   141.6 1405.44   145.7 1404.71   157.7 1404.35
   167.7 1404.95   173.7 1405.86   205.8 1406.13   241.9 1405.12     262 1405.39
   338.2 1404.52   346.2  1405.2   350.3 1405.96   365.2 1410.54   378.3 1414.06
   382.3 1414.62   409.9 1414.95   442.5 1416.72   458.4 1418.11   475.5  1420.2
#Mann= 4 ,-1,0
       0      .1       0   141.6    .045       0   167.7      .1       0
  257.53     .05       0
Bank Sta=141.6,167.7
XS Rating Curve= 0 ,0
Exp/Cntr(USF)=0,0
Exp/Cntr=0.3,0.1

Type RM Length L Ch R = 1 ,1083    ,317.5,305.3,298.4
XS GIS Cut Line= 3
2190769.62267128720191.4285380882190770.71784531720240.711369736
2190756.48058284720737.920382369
#Sta/Elev= 30
       0 1437.23    25.8 1427.33    33.8 1424.79    41.8 1422.69    61.8 1419.21
   109.8 1412.94   117.8    1412   133.7 1410.84   137.8 1409.78     146 1406.17
   149.8 1405.08   154.3 1404.68   169.8 1404.45   209.8 1405.34   233.8 1404.91
   250.6 1405.58     282 1405.34   293.4 1404.97   301.2  1404.3   313.9 1404.42
   318.2  1404.9   321.9 1406.66   325.9 1410.03   329.9 1411.53   345.9 1412.89
   349.9 1413.16   373.9 1413.02   413.8 1411.97   426.2 1412.26   546.7 1421.36
#Mann= 4 ,-1,0
       0      .1       0  249.29     .05       0   293.4    .045       0
   318.2     .05       0
Bank Sta=293.4,318.2
XS Rating Curve= 0 ,0
Exp/Cntr(USF)=0,0
Exp/Cntr=0.3,0.1

Type RM Length L Ch R = 1 ,777     ,270.9,277,270.5
XS GIS Cut Line= 2
2190558.45405454 720140.334678922190548.41714583720701.567174479
#Sta/Elev= 30
       0 1450.55    32.8 1439.66    47.4 1435.44    64.9 1431.05    76.9 1427.16
   104.4 1419.73   116.7 1417.96   128.8    1417   169.6 1415.73   180.9 1414.91
   184.9 1414.29   192.9 1411.79   196.9 1409.99   204.9 1405.53   208.9 1404.53
   220.9 1403.97   236.9 1404.62   256.9 1403.84   286.1 1404.57   288.9 1405.22
   292.9 1407.04     300 1409.28   320.9 1416.45   324.9 1417.39   328.9  1417.7
   356.8 1417.06   381.4 1417.37   436.9 1417.26   482.6 1416.39   561.3 1416.55
#Mann= 4 ,-1,0
       0      .1       0   208.9    .045       0   286.1      .1       0
     300     .05       0
Bank Sta=208.9,286.1
XS Rating Curve= 0 ,0
Exp/Cntr(USF)=0,0
Exp/Cntr=0.3,0.1

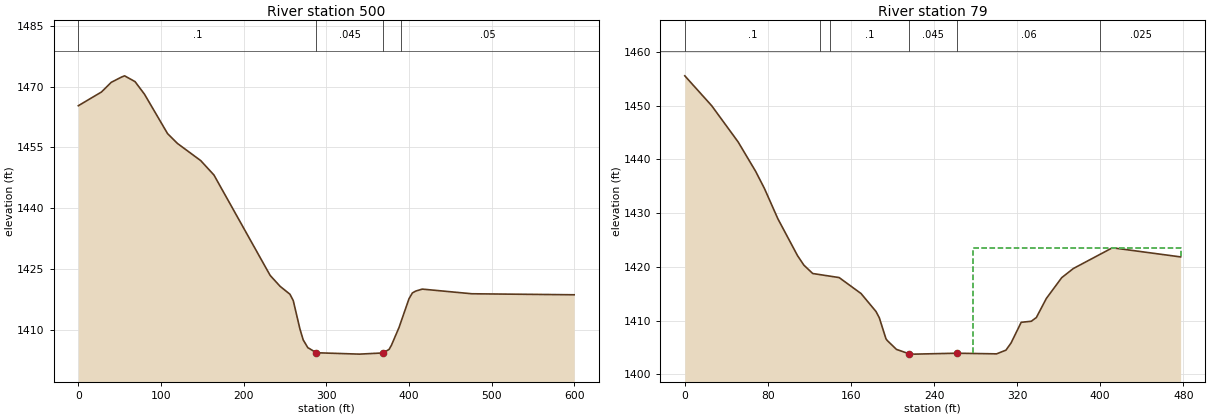
Type RM Length L Ch R = 1 ,500     ,421.4,421,421.4
XS GIS Cut Line= 2
2190297.50799503720049.1856254332190280.80131054 720648.95298591
#Sta/Elev= 30
       0 1465.26      28 1468.65    39.8 1471.03    51.9  1472.3      56 1472.64
    68.6 1471.21      80 1468.12     108 1458.37     120 1455.94   148.1 1451.71
   164.1 1448.16   232.1 1423.38   244.1 1420.69   256.1 1418.72   260.1 1417.14
   268.1  1410.2   272.1 1407.46   277.7 1405.54   288.1 1404.28   340.1 1403.94
   368.91404.233   376.1 1405.12   378.9 1406.14   388.1 1410.53   400.1 1417.59
   404.2 1419.04   408.2  1419.5   416.2 1419.99   476.2 1418.84     600 1418.59
#Mann= 4 ,-1,0
       0      .1       0   288.1    .045       0   368.9      .1       0
     390     .05       0
Bank Sta=288.1,368.9
XS Rating Curve= 0 ,0
Exp/Cntr(USF)=0,0
Exp/Cntr=0.3,0.1

Type RM Length L Ch R = 1 ,79      ,,,
XS GIS Cut Line= 5
 2189941.5060139720220.6474416072189878.70001131720403.882526996
2189920.81939321 720501.742111012190021.81877659720572.319993371
 2190069.7831831720596.978224866
#Sta/Elev= 30
       0 1455.54    25.9 1449.98    51.3 1443.26    68.2 1437.78    76.7 1434.58
    89.6 1428.96   108.5 1422.11   114.7 1420.32   123.2 1418.77   148.6 1418.02
   169.7 1415.05   184.1 1411.71   187.3 1410.53   193.7 1406.63   195.1 1406.28
   203.8 1404.66   216.3 1403.82   221.2 1403.78   261.81403.948   300.2 1403.83
   309.2 1404.52   314.1 1405.84   323.9  1409.7   333.6 1409.89   338.5 1410.59
   348.1 1414.13   362.9    1418   374.1  1419.7   411.7 1423.56   477.4 1421.86
#Mann= 6 ,-1,0
       0      .1       0     130    .025       0     140      .1       0
   216.3    .045       0   261.8     .06       0  400.24    .025       0
#XS Ineff= 2 , 0
                        277.8637         1423.61
Permanent Ineff=
       F       T
Bank Sta=216.3,261.8
XS Rating Curve= 0 ,0
Exp/Cntr(USF)=0,0
Exp/Cntr=0.3,0.1
LCMann Table=0

Chan Stop Cuts=-1
Use User Specified Reach Order=0
Composite Channel Slope=5